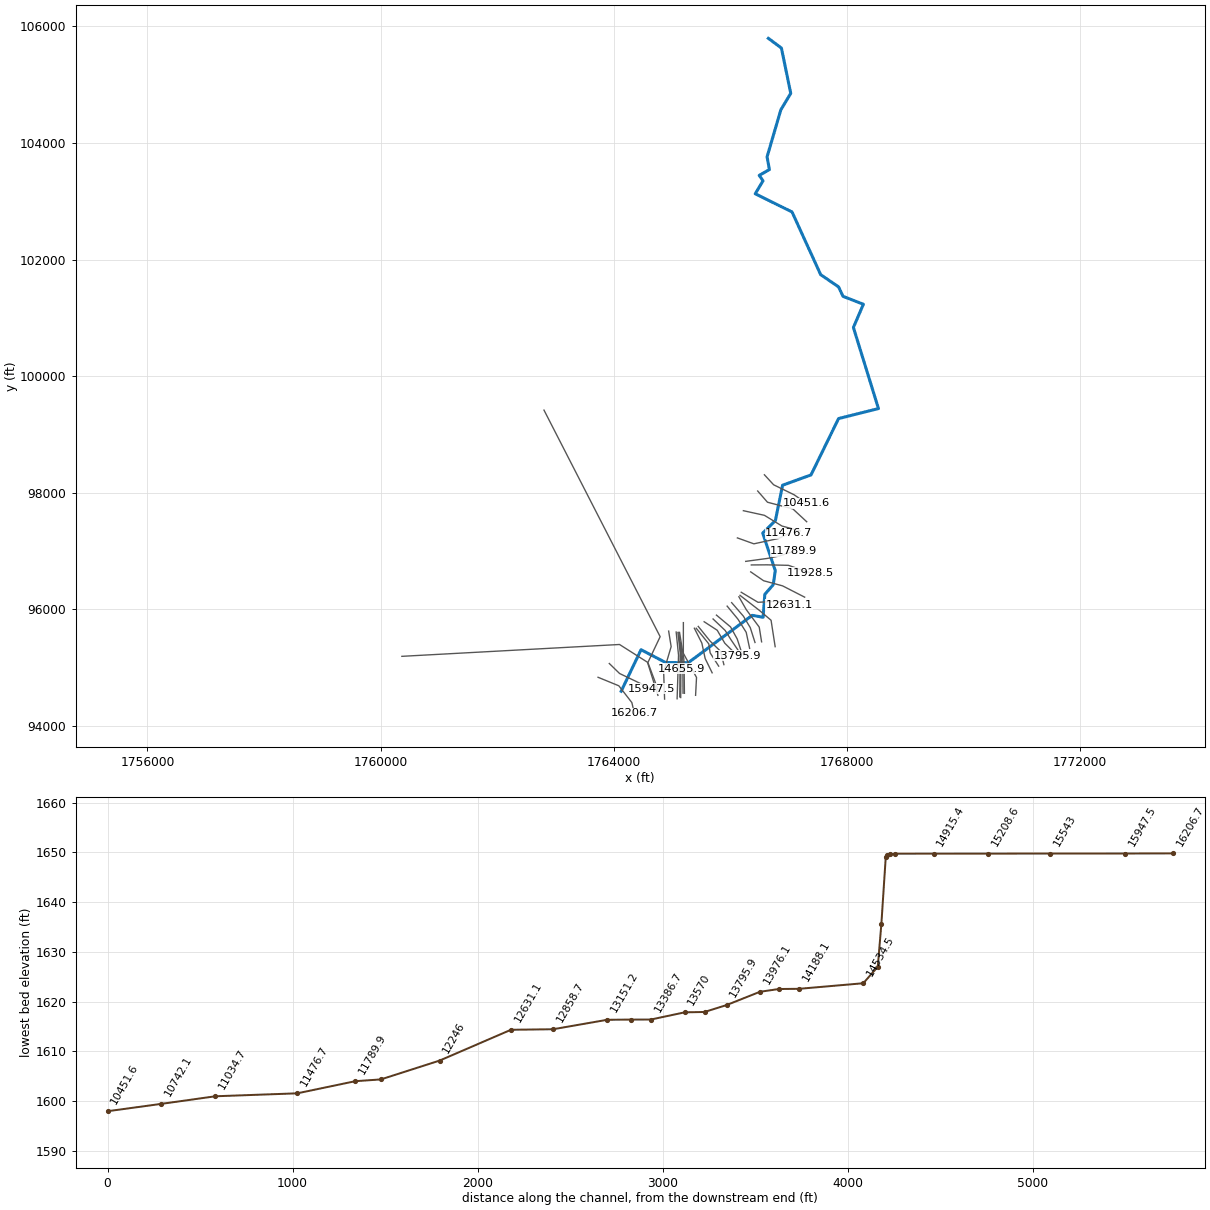
--- War Creek.prj (project) ---

Proj Title=War Creek
Current Plan=p01
Default Exp/Contr=0,0
English Units
Geom File=g01
Flow File=f01
Plan File=p01
BEGIN DESCRIPTION:
END DESCRIPTION:
DSS Export Rating Curves= 0
DSS Export Rating Curve Sorted= 0
DSS Export Volume Flow Curves= 0
DXF OffsetX= 0
DXF OffsetY= 0
DXF ScaleX= 0
DXF ScaleY= 0

--- War Creek.p01 (plan) ---

Plan Title=Floodplain
Program Version=4.00
Geom File=g01
Flow File=f01
K Sum by GR=0
Std Step Tol=0.01
Critical Tol=0.01
Num of Std Step Trials=20
Max Error Tol=0.3
Flow Tol Ratio=0.001
Split Flow NTrial=30
Split Flow Tol=0.02
Split Flow Ratio=0.02
Log Output Level=0
Friction Slope Method=1
Unsteady Friction Slope Method=2
Unsteady Bridges Friction Slope Method=1
Global Log Level=0
CheckData=False
Run HTab=0
Run UNet=0
Run PostProcess=0
UNET Theta=0
UNET Theta Warmup=0
UNET ZTol=0
UNET ZSATol=0
UNET MxIter=0
UNET MaxInSteps=0
UNET DtIC=0
UNET DtMin=0
UNET MaxCRTS=0
UNET WFStab=0
UNET SFStab=0
UNET WFX=0
UNET SFX=0
UNET DSS MLevel=0
UNET DZMax Abort=0
UNET Convert EG Bridges=0
UNET Use Existing IB Tables=0
UNET Froude Limit=0
UNET Froude Power=0
Write IC File=0
Echo Input=False
Echo Output=False
Write Detailed=0

--- War Creek.f01 (steady flow) ---

Flow Title=NFF Regression Equation
Program Version=4.00
Number of Profiles=1
Profile Names=P100yr
River Rch & RM=War Creek,Main      ,16206.7
576.1014
River Rch & RM=War Creek,Main      ,15208.6
1646.326
River Rch & RM=War Creek,Main      ,12246
1741.968
River Rch & RM=War Creek,Main      ,11476.7
1769.675
Boundary for River Rch & Prof#=War Creek,Main      ,1
Up Type=0
Dn Type=3
Dn Slope=0.012392

--- War Creek.g01 (geometry) ---

Geom Title=USGS 10m DEM
Program Version=4.00

River Reach=War Creek       ,Main
Reach XY= 30
     1764128.886       94597.019      1764469.79       95308.927
     1764891.196       95089.669     1765279.082         95085.2
     1766377.496       95898.509     1766564.289       95865.441
     1766593.783       96257.795      1766738.57       96424.032
     1766773.426        96664.45     1766557.217       97308.505
     1766775.213        97523.34     1766898.631       98129.206
     1767386.524       98306.043     1767859.208       99272.578
     1768544.093       99443.726     1768114.068      100834.241
     1768285.273      101232.379     1767936.023      101368.374
     1767858.721      101530.959     1767552.504      101739.924
     1767060.762      102815.673     1766429.377      103126.877
     1766563.035      103349.308     1766497.594      103442.082
     1766672.255      103541.816     1766632.856      103761.255
     1766868.254      104564.699     1767038.818      104848.973
     1766878.727      105625.486     1766655.236      105792.322

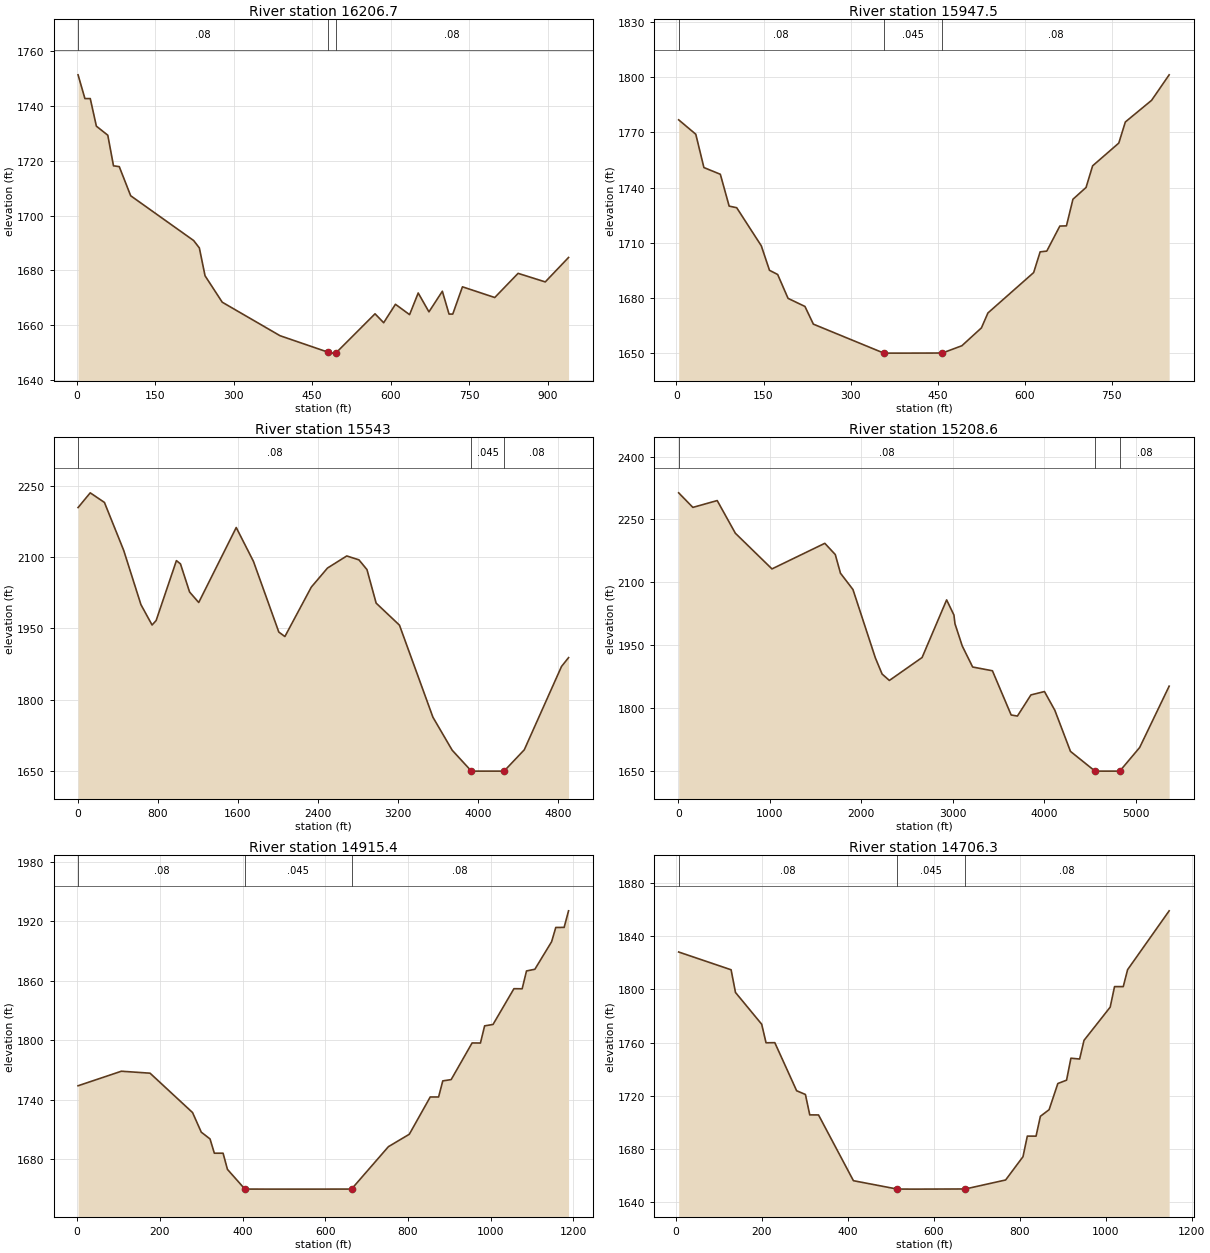
Type RM Length L Ch R = 1 ,16206.7 ,248.1,259.2,270.3
XS GIS Cut Line= 4
     1763732.137       94836.377     1764088.911       94690.228
     1764312.432        94402.23     1764355.417       94217.395
#Sta/Elev= 30
     2.9  1751.4      16 1742.73    26.2 1742.73    37.9 1732.65    59.7 1729.36
    70.6 1718.18    81.6 1717.89   103.4 1707.26   223.7 1690.91   234.6 1688.21
   245.5 1678.04   278.3  1668.4   388.7 1656.17   480.2 1650.17   487.7 1649.81
   495.2 1649.82   570.2 1664.16   586.7 1660.91   609.2 1667.64   636.2 1663.86
   652.7 1671.76   673.2 1664.87   698.8  1672.4   711.6 1664.06   718.7 1664.06
   737.2 1674.02   798.9 1670.11   843.5 1678.93   895.4 1675.81   939.9 1684.73
#Mann= 3 , 0 , 0
     2.9     .08       0   480.2    .045       0   495.2     .08       0
Bank Sta=480.2,495.2
XS Rating Curve= 0 ,0
Exp/Cntr=0.3,0.1

Type RM Length L Ch R = 1 ,15947.5 ,407.2,404.5,401.9
XS GIS Cut Line= 4
     1763925.409       95072.561     1764101.806       94900.854
     1764389.805       94763.303     1764644.043       94637.439
#Sta/Elev= 30
     3.8 1776.87    33.3 1769.03    47.3 1750.88    75.6 1747.22    90.8 1729.88
   103.8    1729   146.2 1708.25   160.3 1694.91   174.4 1692.63   192.3 1679.62
   221.4 1675.22   235.9 1665.58   357.3  1649.8   386.9 1649.79   458.2 1649.85
   491.8 1653.81   525.5 1663.53   536.7 1671.67   615.5 1693.67   626.7 1704.96
   638.1 1705.36   660.6    1719     672 1719.12   683.2 1733.61   705.8 1740.04
   717.1 1751.82   762.2  1764.2   773.5 1775.71   818.7 1787.49     849 1801.39
#Mann= 3 , 0 , 0
     3.8     .08       0   357.3    .045       0   458.2     .08       0
Bank Sta=357.3,458.2
XS Rating Curve= 0 ,0
Exp/Cntr=0.3,0.1

Type RM Length L Ch R = 1 ,15543   ,371.8,334.4,305.3
XS GIS Cut Line= 4
     1760365.587       95195.526     1764100.256       95398.647
     1764580.107         95094.1     1764759.474       94526.886
#Sta/Elev= 30
     2.9 2204.45   124.5 2235.47   266.3 2215.26   458.8 2114.42     631 2000.23
   742.4 1957.29   782.9 1966.74   985.5 2092.79    1026 2085.96  1117.2 2026.72
  1208.4 2004.71  1583.2 2162.46  1755.4 2091.09  2008.7 1942.43  2069.4 1933.06
  2332.8 2036.93  2494.9 2077.17  2687.4 2102.61  2808.9 2094.44  2889.3 2073.92
  2981.1 2003.32  3214.1 1956.95  3548.4 1763.19    3741 1693.73  3932.7 1649.81
  3969.2 1649.78  4259.3  1649.8  4461.2 1694.73  4832.9    1870  4903.4 1888.64
#Mann= 3 , 0 , 0
     2.9     .08       0  3932.7    .045       0  4259.3     .08       0
Bank Sta=3932.7,4259.3
XS Rating Curve= 0 ,0
Exp/Cntr=0.3,0.1

Type RM Length L Ch R = 1 ,15208.6 ,289.5,293.2,296.9
XS GIS Cut Line= 4
     1762804.405       99417.567     1764797.819       95532.477
     1764587.596       95089.419     1764764.017       94616.451
#Sta/Elev= 30
       4 2313.46   159.1 2278.72     425 2295.01   623.2 2217.11  1023.2 2132.01
  1600.4 2193.05  1714.7  2166.3  1771.5 2121.76  1907.9 2082.85  2153.3 1919.39
  2226.3 1881.28  2305.8 1866.03  2662.9 1920.68  2931.1 2058.09  3010.7 2022.11
  3022.1 2001.34  3101.7 1948.27  3215.3 1898.06  3431.4  1889.1    3636 1783.66
  3704.2 1781.09    3852 1831.54  3999.8 1839.55  4113.5 1794.66    4284 1696.85
  4552.2  1649.8  4668.3 1649.77  4822.7  1649.8  5039.8 1706.18  5361.9  1852.4
#Mann= 3 , 0 , 0
       4     .08       0  4552.2    .045       0  4822.7     .08       0
Bank Sta=4552.2,4822.7
XS Rating Curve= 0 ,0
Exp/Cntr=0.3,0.1

Type RM Length L Ch R = 1 ,14915.4 ,202.6,209.1,215.7
XS GIS Cut Line= 4
     1764943.772       95628.372     1764986.592       95361.981
     1764857.802       94929.869     1764873.921       94462.409
#Sta/Elev= 30
     2.2 1754.08     107 1768.75   176.3 1766.77   279.1 1727.03   300.2 1707.22
   321.3 1700.44   331.8 1686.01   352.9 1686.01   363.5 1669.68   405.7  1649.8
   553.5 1649.76   663.6 1649.82   752.7 1692.59   803.3 1705.16   853.9 1742.76
   874.1 1742.75   884.2 1758.99   904.5  1760.3   955.1 1797.28   975.3 1797.21
   985.4 1814.53  1005.7 1815.94  1056.3 1852.04  1076.2 1851.94  1086.7 1869.94
  1106.9 1871.63  1147.4 1899.44  1157.5 1913.82  1177.7  1913.9  1188.4 1930.62
#Mann= 3 , 0 , 0
     2.2     .08       0   405.7    .045       0   663.6     .08       0
Bank Sta=405.7,663.6
XS Rating Curve= 0 ,0
Exp/Cntr=0.3,0.1

Type RM Length L Ch R = 1 ,14706.3 ,28.8,28.9,29
XS GIS Cut Line= 3
     1765072.726       95612.253     1765113.294       95214.162
     1765088.845       94467.782
#Sta/Elev= 30
     6.3 1828.15   128.3 1814.78   138.5 1797.72   199.5  1773.8   209.6 1759.85
     230 1759.94   280.8 1723.76   301.2 1720.97   311.3 1705.61   331.7 1705.56
   412.9 1656.09   514.5 1649.81   554.5 1649.75   673.3 1649.87     767 1656.63
   807.4 1674.15   817.5 1689.64   837.8 1689.61   847.9 1704.54   868.2 1709.52
   888.5  1729.2   908.8 1731.73   918.9 1748.24   939.2 1747.64   949.4 1761.68
  1010.3 1786.67  1020.4 1802.12  1040.7 1802.11  1050.8 1814.85  1147.5 1859.13
#Mann= 3 , 0 , 0
     6.3     .08       0   514.5    .045       0   673.3     .08       0
Bank Sta=514.5,673.3
XS Rating Curve= 0 ,0
Exp/Cntr=0.3,0.1

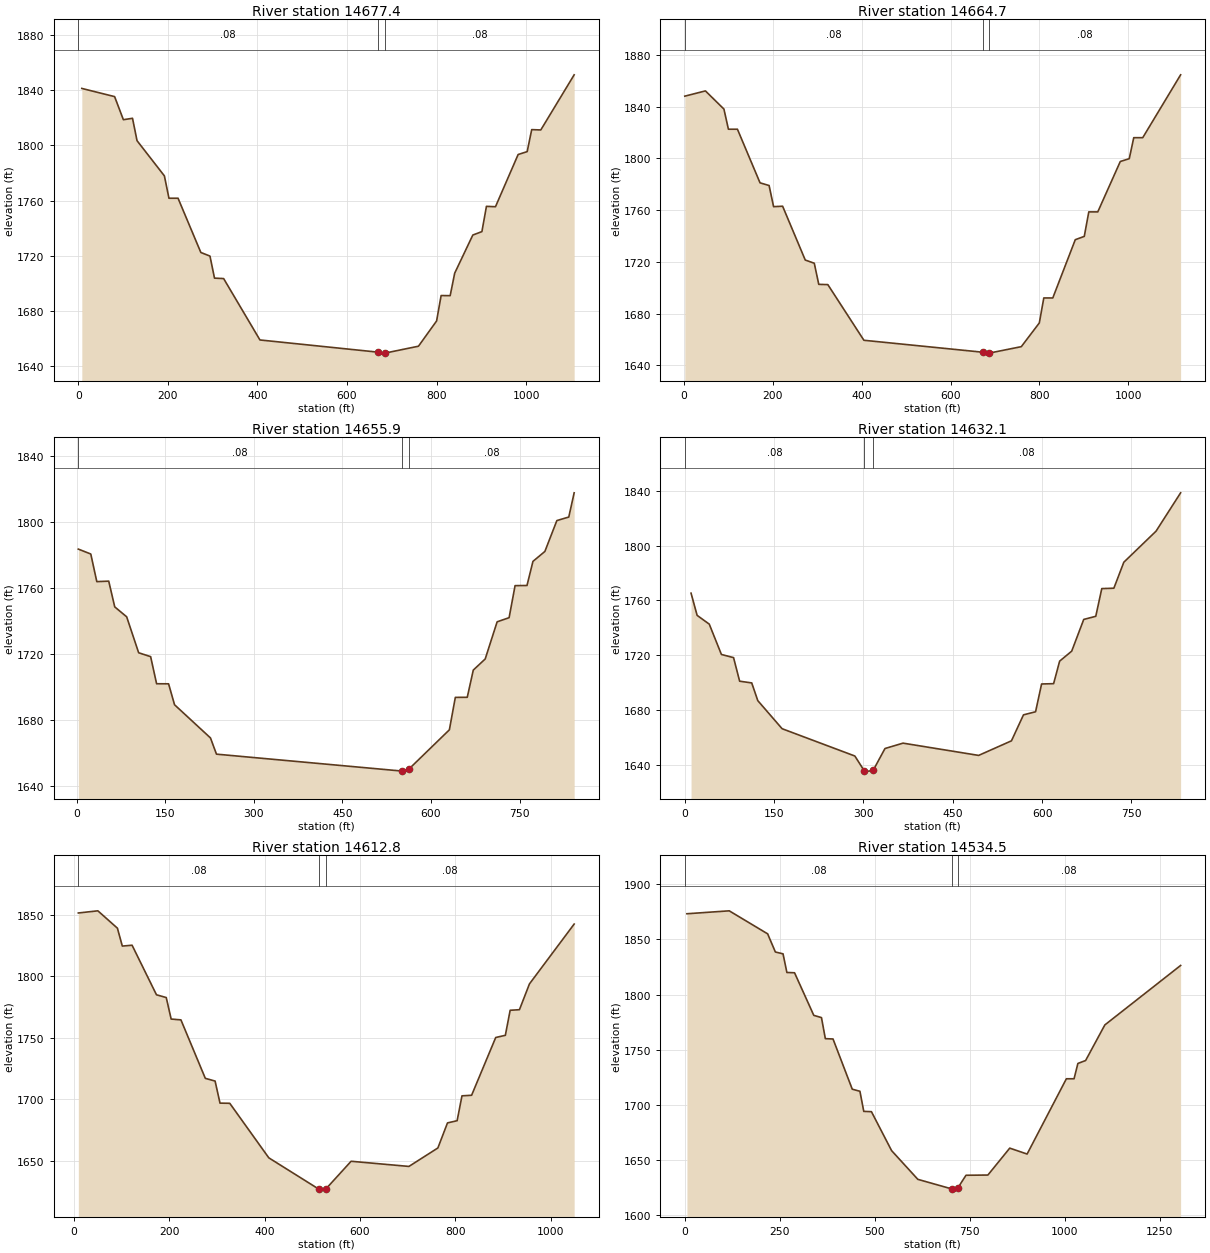
Type RM Length L Ch R = 1 ,14677.4 ,12.7,12.7,12.7
XS GIS Cut Line= 3
     1765102.736       95604.827      1765141.45       95256.396
     1765134.411       94499.704
#Sta/Elev= 30
     7.8 1841.31      81 1835.39   100.6 1818.66     121 1819.68   131.1 1803.47
   192.2 1777.98   202.4 1761.78   222.7 1761.78   273.6  1722.5     294 1719.88
   304.1 1703.92   324.5 1703.61   405.6 1659.14   669.8 1650.29   677.3 1649.61
   684.8 1649.62   759.6 1654.62   800.1 1672.91   810.2 1691.31   830.4 1691.22
   840.5  1707.5     881 1735.13   901.3 1737.61   911.4 1755.92   931.6 1755.64
   982.2 1793.44  1002.4 1795.55  1012.5 1811.47  1032.8 1811.24  1107.3 1851.16
#Mann= 3 , 0 , 0
       0     .08       0   669.8    .045       0   684.8     .08       0
Bank Sta=669.8,684.8
XS Rating Curve= 0 ,0
Exp/Cntr=0.3,0.1

Type RM Length L Ch R = 1 ,14664.7 ,8.4,8.8,9.2
XS GIS Cut Line= 3
     1765118.911       95604.827     1765154.106        95231.76
     1765150.587       94489.145
#Sta/Elev= 30
     2.3 1847.98    48.7 1852.05    90.3 1838.01   100.4 1822.45   120.7 1822.45
   171.5 1781.03   191.9 1778.95     202 1762.61   222.3 1762.96   273.2 1721.38
   293.5  1718.9   303.6  1702.6     324 1702.39   405.1 1659.39   671.9 1650.18
   679.4 1649.46   686.9 1649.47   759.1 1654.46   799.6 1672.77   809.7 1692.09
   829.9 1692.07   880.5  1737.1   900.7 1739.64   910.9 1758.58   931.1 1758.58
   981.7 1797.49  1001.9 1799.69    1012 1815.91  1032.2 1815.91  1117.4 1864.47
#Mann= 3 , 0 , 0
     2.3     .08       0   671.9    .045       0   686.9     .08       0
Bank Sta=671.9,686.9
XS Rating Curve= 0 ,0
Exp/Cntr=0.3,0.1

Type RM Length L Ch R = 1 ,14655.9 ,24.2,23.8,23.4
XS GIS Cut Line= 3
     1765143.477       95437.364     1765161.561        95169.74
     1765164.606       94982.284
#Sta/Elev= 30
     2.5 1783.67    23.6 1780.69    33.8 1763.96      54 1764.25    64.2 1748.64
    84.4 1742.63   104.7 1720.84     125 1718.48   135.1 1702.06   155.4 1702.02
   165.5 1689.33   226.4 1669.21   236.5 1659.39   551.2 1649.12   558.7  1649.1
   561.9 1650.11   631.1 1674.13   641.2 1693.79   661.4 1693.86   671.6 1710.33
   691.8 1717.08     712 1739.59   732.3 1742.11   742.4 1761.52   762.6 1761.62
   772.7 1776.23   792.9 1782.25   813.2 1800.96   833.4  1803.1   842.5 1817.78
#Mann= 3 , 0 , 0
     2.5     .08       0   551.2    .045       0   561.9     .08       0
Bank Sta=551.2,561.9
XS Rating Curve= 0 ,0
Exp/Cntr=0.3,0.1

Type RM Length L Ch R = 1 ,14632.1 ,18.7,19.3,20
XS GIS Cut Line= 3
      1765153.45        95393.88     1765186.691       95129.024
     1765190.771       94563.254
#Sta/Elev= 30
    10.5 1765.32    20.7 1749.12    41.1 1742.73    61.5 1720.62    81.9 1718.31
    92.1 1701.13   112.4 1699.87   122.6 1686.96   163.4  1666.5   285.6 1646.58
   301.7 1635.61   309.2 1635.57   316.7 1636.42   336.2 1652.05   366.5 1655.97
   493.5 1647.03   548.6 1657.66   568.8  1676.6   589.1 1678.85   599.2  1699.1
   619.4 1699.33   629.5 1715.74   649.8 1723.05     670 1746.17   690.2 1748.44
   700.3 1768.64   720.6 1768.92   737.3 1787.86   791.4  1810.5   832.7 1838.46
#Mann= 3 , 0 , 0
       0     .08       0   301.7    .045       0   316.7     .08       0
Bank Sta=301.7,316.7
XS Rating Curve= 0 ,0
Exp/Cntr=0.3,0.1

Type RM Length L Ch R = 1 ,14612.8 ,66.7,78.3,89.8
XS GIS Cut Line= 4
      1765130.69       95604.607     1765204.041       95154.587
     1765209.531       94965.863     1765214.272       94561.378
#Sta/Elev= 30
     8.8 1851.45    49.8  1853.2    90.8  1839.1   101.1 1824.55   121.6 1825.24
   172.8 1784.95   193.3 1782.72   203.6 1765.24   224.1 1764.57   275.3 1717.04
   295.8 1714.84   306.1 1696.91   326.6 1696.76   408.5 1652.45     513 1627.11
   522.9 1627.01     528 1627.02   581.2 1649.65   702.6 1645.46   763.3 1660.46
   783.5 1680.83   803.7 1682.62   813.9 1702.84   834.1 1703.29   884.7 1750.24
   904.9 1752.03     915 1772.37   934.5 1772.85   955.5 1793.81  1049.3 1842.44
#Mann= 3 , 0 , 0
     8.8     .08       0     513    .045       0     528     .08       0
Bank Sta=513,528
XS Rating Curve= 0 ,0
Exp/Cntr=0.3,0.1

Type RM Length L Ch R = 1 ,14534.5 ,352.9,346.4,339.9
XS GIS Cut Line= 4
     1765196.307       95773.446     1765195.698       95248.609
     1765421.978       94833.153     1765405.858       94526.886
#Sta/Elev= 30
     5.6 1873.21   116.9 1875.86     218    1855   238.3 1838.56   258.5 1836.88
   268.6    1820   288.8 1819.73   339.4 1781.15   359.6 1779.12   369.8 1760.04
     390 1759.74   440.6 1714.26   460.8 1712.35   470.9 1694.14   491.1 1693.87
   544.1  1658.6   613.2 1632.55   702.9 1623.85   710.4  1623.7   717.9 1624.46
   739.9 1636.26   797.5 1636.46     855 1660.85   900.7 1655.48    1004 1723.69
  1024.2 1723.69  1034.3 1737.57  1054.6 1740.21  1105.2 1772.46  1304.6 1826.36
#Mann= 3 , 0 , 0
       0     .08       0   702.9    .045       0   717.9     .08       0
Bank Sta=702.9,717.9
XS Rating Curve= 0 ,0
Exp/Cntr=0.3,0.1

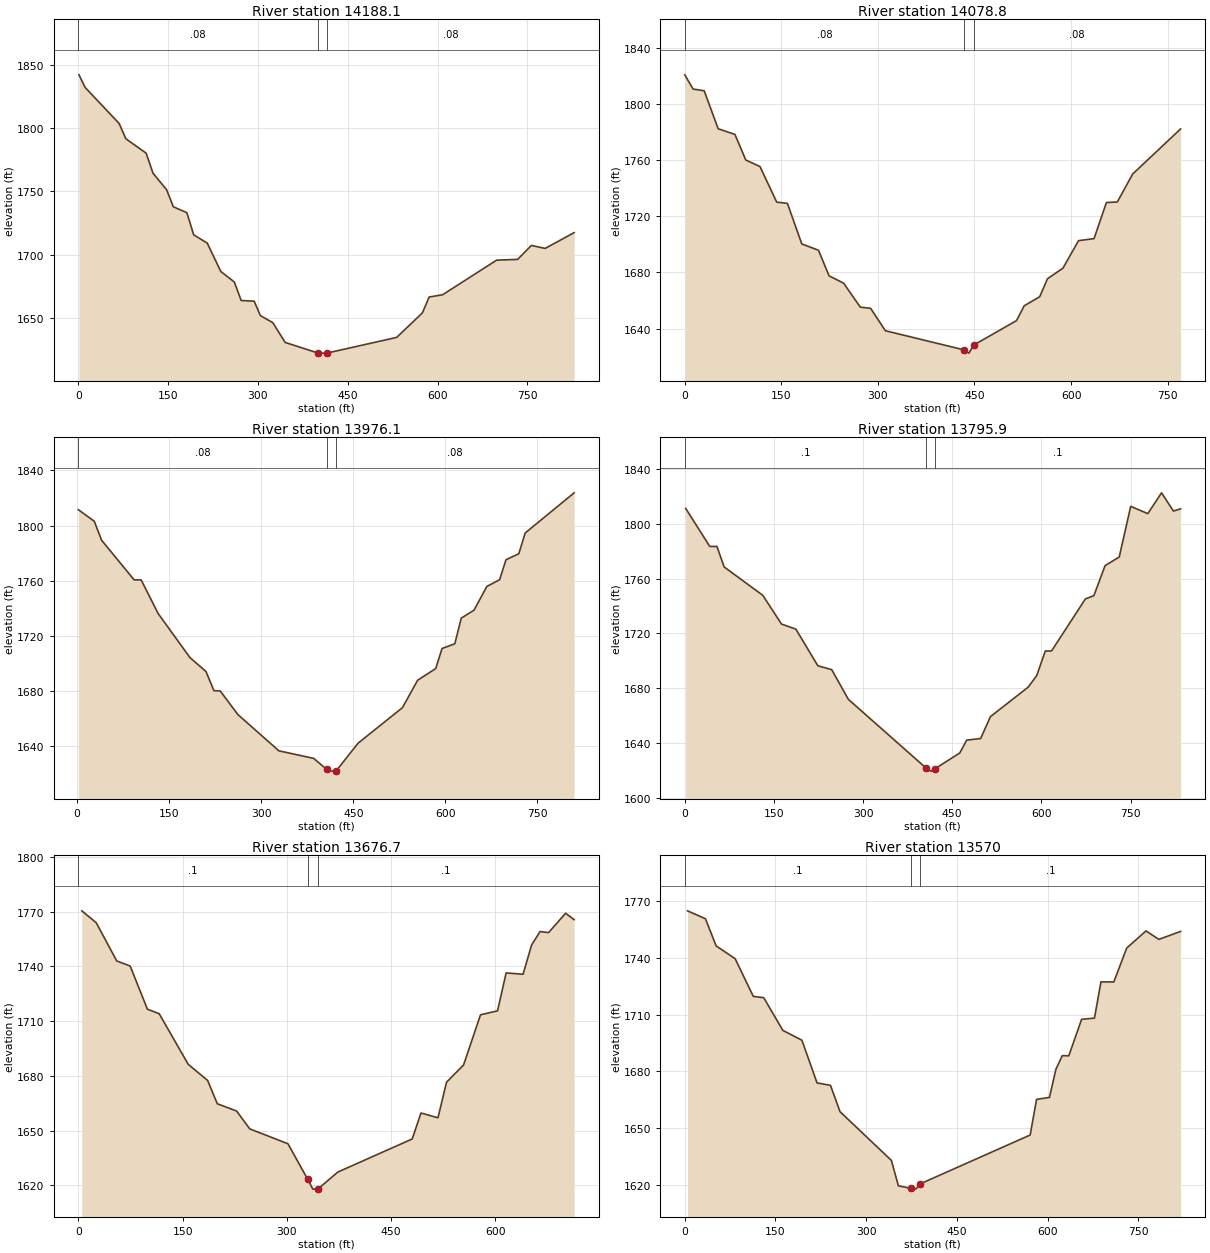
Type RM Length L Ch R = 1 ,14188.1 ,110.7,109.3,107.9
XS GIS Cut Line= 4
     1765385.092       95676.903     1765513.197       95422.693
     1765569.905       95158.493     1765690.107       94913.001
#Sta/Elev= 30
     1.1 1841.89    11.4 1831.92    68.1 1803.59    79.4 1791.52   113.3 1780.15
   124.7 1764.39   147.4 1751.38   158.7  1737.9   181.3 1733.27   192.7 1715.82
   215.3 1709.29     238 1686.93   260.6 1678.61     272 1664.07   293.8 1663.49
   304.1 1652.12   324.8 1646.62   345.5    1631   400.1 1622.71   407.6 1622.58
   415.1  1622.6   531.7 1634.96   574.7 1654.29     586  1666.8   608.5 1668.58
   698.6 1695.82   733.8 1696.46   756.8 1707.44   779.8  1705.1   828.2 1717.54
#Mann= 3 , 0 , 0
       0     .08       0   400.1    .045       0   415.1     .08       0
Bank Sta=400.1,415.1
XS Rating Curve= 0 ,0
Exp/Cntr=0.3,0.1

Type RM Length L Ch R = 1 ,14078.8 ,87.9,102.7,117.4
XS GIS Cut Line= 4
     1765417.072       95677.073     1765632.843       95408.417
     1765656.112       95253.993     1765802.075       95027.646
#Sta/Elev= 30
      .4 1820.71    13.3 1810.59    30.5 1809.35    52.2  1782.3    78.2 1778.29
    95.1 1760.04   117.1 1755.38   143.1 1730.05   159.7 1729.16     182 1700.29
   207.9 1695.81   224.3 1677.58   246.9 1672.37   272.8 1655.31   288.9 1654.43
   311.7  1638.5   433.9 1624.85   441.4 1622.54   448.9 1628.29   515.2 1645.67
   527.2 1656.25   551.3 1662.72   563.3 1675.49   587.4 1683.04   611.5 1702.63
   635.6 1704.06   654.8 1729.78   671.7 1730.16   695.7 1750.15     770 1782.19
#Mann= 3 , 0 , 0
      .4     .08       0   433.9    .045       0   448.9     .08       0
Bank Sta=433.9,448.9
XS Rating Curve= 0 ,0
Exp/Cntr=0.3,0.1

Type RM Length L Ch R = 1 ,13976.1 ,186.3,180.2,174.1
XS GIS Cut Line= 4
     1765451.606       95708.652     1765653.977       95457.888
     1765834.352       95281.913     1765891.544       95053.145
#Sta/Elev= 30
     1.9 1811.51    27.9 1803.11    39.8 1789.36    92.9 1760.61   104.3 1760.61
   131.9 1736.29   183.9 1704.24   209.9 1694.23   222.9 1680.29   233.1 1680.15
   261.9 1663.01   328.8 1636.68   385.4 1631.24   406.8 1623.22   414.3 1621.98
   421.8 1621.99   457.8 1642.22   530.2 1668.03   554.9 1687.87   584.3 1696.32
   594.7 1710.87   615.5  1714.3     626 1732.89   646.8 1738.66   667.7 1755.86
   688.5  1760.7   698.9 1775.19   719.8 1779.58   730.2 1794.61     810 1823.72
#Mann= 3 , 0 , 0
     1.9     .08       0   406.8    .045       0   421.8     .08       0
Bank Sta=406.8,421.8
XS Rating Curve= 0 ,0
Exp/Cntr=0.3,0.1

Type RM Length L Ch R = 1 ,13795.9 ,118.5,119.2,120
XS GIS Cut Line= 4
     1765552.662       95788.883      1765777.16       95642.661
     1765906.943       95420.555     1766126.513       95203.001
#Sta/Elev= 30
     1.5 1811.29      42  1783.5    54.1  1783.5    66.2 1768.51   131.2 1747.78
   162.7 1726.79     187 1723.04   223.9 1696.29   247.2 1693.46   275.2 1671.78
   406.5 1621.35     414 1619.31   421.5 1621.18   462.7 1632.58   474.4 1641.99
   497.8 1643.12   514.3 1659.13   577.9 1680.72   592.2 1689.14   606.6 1707.08
   617.1 1707.08   674.1 1745.18   688.3 1747.51   707.2 1769.47     731 1775.76
   750.3 1812.78   779.1 1807.47   802.2 1822.66   822.2 1809.34   834.3 1810.99
#Mann= 3 , 0 , 0
       0      .1       0   406.5    .045       0   421.5      .1       0
Bank Sta=406.5,421.5
XS Rating Curve= 0 ,0
Exp/Cntr=0.3,0.1

Type RM Length L Ch R = 1 ,13676.7 ,108,106.7,105.5
XS GIS Cut Line= 4
     1765705.666       95836.112     1765912.909       95640.071
      1766016.53       95474.837     1766148.158       95281.597
#Sta/Elev= 30
       5 1770.47    25.8 1763.94    55.2 1743.01    74.6  1740.2    99.4 1716.54
   116.3 1714.09   158.1 1686.33     186 1677.51   199.9 1664.72   227.7 1660.74
   246.6 1650.96   301.6 1642.77   329.9 1623.36   337.4 1617.92   344.9 1618.05
   373.3 1627.28   480.3 1645.41     493 1659.65   517.4 1657.02   529.7 1676.53
   554.2 1685.97   578.6 1713.49   603.1 1715.64   615.4 1736.43   639.8  1735.7
   652.1 1751.76   664.3 1759.13   676.5 1758.53     701 1769.14   713.3 1765.62
#Mann= 3 , 0 , 0
       0      .1       0   329.9    .045       0   344.9      .1       0
Bank Sta=329.9,344.9
XS Rating Curve= 0 ,0
Exp/Cntr=0.3,0.1

Type RM Length L Ch R = 1 ,13570   ,182,183.3,184.6
XS GIS Cut Line= 4
     1765763.962       95902.225     1766005.927       95699.853
     1766120.311       95493.083     1766203.899       95237.919
#Sta/Elev= 30
     4.5 1764.82    34.2 1760.63    51.8 1746.32    83.3 1739.54   113.3 1719.63
   130.6 1718.95   162.2 1701.68   193.7 1696.49   218.8 1673.93     241 1672.67
   256.8 1658.74   341.8 1633.01   353.3 1619.59   374.6 1618.24   382.1 1617.85
   389.6 1620.65   571.3 1646.42   581.9 1665.25   603.2 1666.28   613.9 1681.16
   624.5 1688.35   635.2 1688.24   656.4 1707.51   677.7 1708.17   688.4 1727.31
   709.7 1727.25     731 1745.15   762.9 1754.21   784.2 1749.74   820.2 1753.96
#Mann= 3 , 0 , 0
       0      .1       0   374.6    .045       0   389.6      .1       0
Bank Sta=374.6,389.6
XS Rating Curve= 0 ,0
Exp/Cntr=0.3,0.1

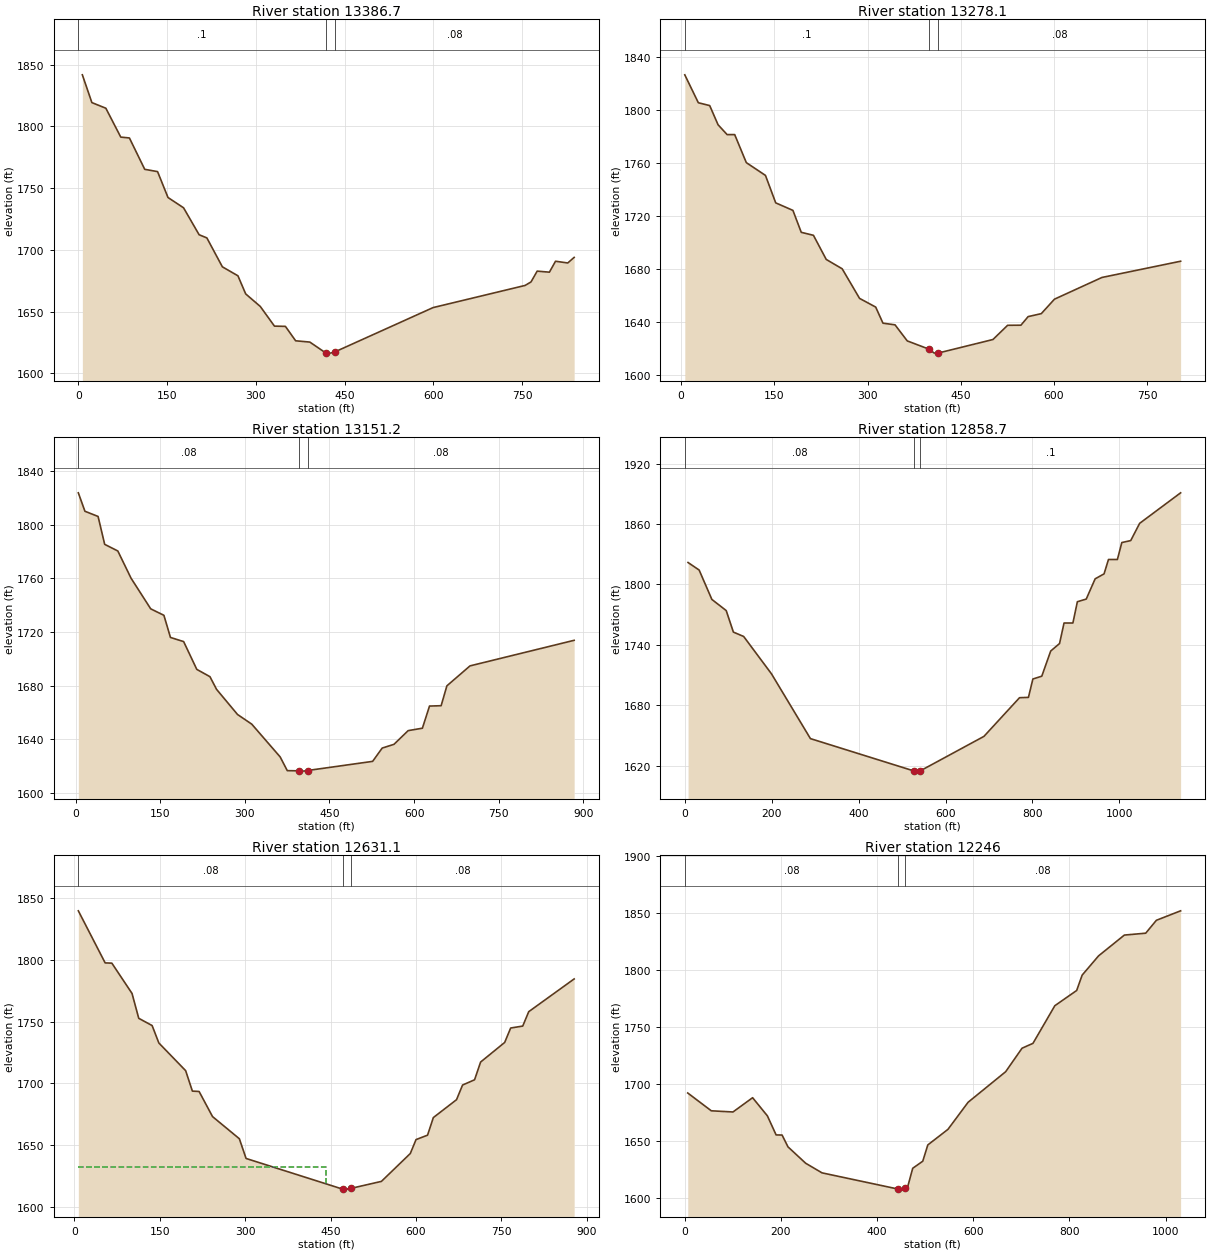
Type RM Length L Ch R = 1 ,13386.7 ,110.8,108.6,107.2
XS GIS Cut Line= 4
     1765947.567       96056.542     1766133.509       95831.835
     1766274.289       95607.467     1766333.185       95332.395
#Sta/Elev= 30
     6.8 1841.76    22.9 1819.27    46.5 1814.71    71.7 1791.33    86.3 1790.64
   112.2 1765.23   133.9 1763.38   151.5 1742.42   177.8 1734.09   204.1 1712.27
   217.2  1709.7   243.4 1686.28   269.7 1679.02   282.8 1664.35   307.5 1654.17
   331.4 1638.26   349.9 1638.07   367.2 1626.38   391.1 1625.36   418.5 1616.41
     426  1616.4   433.5  1617.4   599.4 1653.27   754.9 1671.21   764.9 1674.05
   775.3 1682.79     796 1681.95   806.3 1690.81     827 1689.41   837.8 1693.93
#Mann= 3 , 0 , 0
       0      .1       0   418.5    .045       0   433.5     .08       0
Bank Sta=418.5,433.5
XS Rating Curve= 0 ,0
Exp/Cntr=0.3,0.1

Type RM Length L Ch R = 1 ,13278.1 ,123,126.8,129.8
XS GIS Cut Line= 4
     1766024.932       96116.171     1766226.574       95883.722
     1766344.199       95687.681     1766425.415       95432.828
#Sta/Elev= 30
     5.9 1826.21    27.7 1805.15      46 1803.02    59.4 1788.59      74 1781.14
    86.2 1781.14   104.9 1760.02   135.7 1750.39   152.2 1729.69   179.9 1724.01
   193.3 1707.47   212.9 1705.23   233.5 1687.03   259.2 1679.96   287.1 1657.67
   313.1 1651.11   324.8 1638.97   344.2 1637.72   363.9 1625.61   398.4 1619.46
   407.5 1616.39   413.4 1616.42   501.8 1626.65   525.4 1637.37   546.8 1637.44
   558.4 1643.91   579.6 1646.17   600.8 1657.07   677.2 1673.44   803.8 1685.68
#Mann= 3 , 0 , 0
     5.9      .1       0   398.4    .045       0   413.4     .08       0
Bank Sta=398.4,413.4
XS Rating Curve= 0 ,0
Exp/Cntr=0.3,0.1

Type RM Length L Ch R = 1 ,13151.2 ,287.3,292.5,297.7
XS GIS Cut Line= 4
     1766148.837       96217.091      1766276.91       95994.105
     1766497.947       95696.757     1766538.659       95443.997
#Sta/Elev= 30
     4.8 1823.66    16.5 1809.93    39.8 1806.06    51.5 1785.29    74.8 1780.34
    98.2 1760.11   133.1 1737.24   156.5 1732.42   168.1 1715.94   191.5 1712.83
   214.8 1692.14   238.1 1686.71   249.8 1677.29     287 1658.54   312.2 1651.36
   362.6 1626.91   375.2  1616.7   396.1 1616.57   403.6 1616.35   411.1 1616.81
   526.5 1623.62   543.4 1633.52   564.3 1636.31   589.5 1646.52   614.7 1648.32
   627.3 1664.82   647.9 1665.08   658.1 1679.88   699.1 1694.75   883.7  1713.8
#Mann= 3 , 0 , 0
     4.8     .08       0   396.1    .045       0   411.1     .08       0
Bank Sta=396.1,411.1
XS Rating Curve= 0 ,0
Exp/Cntr=0.3,0.1

Type RM Length L Ch R = 1 ,12858.7 ,210.6,227.7,244.8
XS GIS Cut Line= 4
     1766168.704       96240.977     1766503.057       95981.413
     1766701.029       95814.237     1766771.419       95361.102
#Sta/Elev= 30
     7.4 1821.82      33 1814.32    62.3  1785.1    95.3 1774.04   111.8 1752.65
   135.5 1748.27   199.5 1711.14   289.1 1646.77   527.3 1614.62   534.8 1614.45
   542.3 1614.83   688.4 1648.98   770.3 1687.43   790.8 1687.75     801 1706.02
   821.5 1708.81     842  1733.8   862.4 1741.27   872.7 1761.65   893.1 1761.68
   903.4 1782.82   923.8 1785.45   944.3 1805.58   964.8  1810.5     975  1824.8
   995.5  1824.8  1005.7 1841.64  1026.2  1843.6  1046.7 1860.73    1141 1891.06
#Mann= 3 , 0 , 0
       0     .08       0   527.3    .045       0   542.3      .1       0
Bank Sta=527.3,542.3
XS Rating Curve= 0 ,0
Exp/Cntr=0.3,0.1

Type RM Length L Ch R = 1 ,12631.1 ,392.6,385.1,377.7
XS GIS Cut Line= 4
     1766188.864       96294.172     1766476.661       96122.193
     1766806.614       96139.791     1767009.588       96078.406
#Sta/Elev= 30
     6.9 1839.77      54  1797.6    65.8 1797.38   101.2 1772.85     113 1752.71
   136.5 1746.84   148.3 1732.73   195.4 1710.29   207.2 1693.75     219 1693.43
   242.6 1673.09   289.7 1655.16   301.5 1639.18   470.9 1614.38   478.4 1614.34
   485.9 1614.97   539.2 1620.61   589.9 1643.17     600 1654.47   620.2 1658.04
   630.4  1672.3   671.1 1686.78   681.7 1698.64   702.8 1702.91   713.4 1717.27
   755.7 1733.15   766.2 1744.84   787.4 1746.42   797.9 1758.07   877.7  1784.6
#Mann= 3 , 0 , 0
     6.9     .08       0   470.9    .045       0   485.9     .08       0
#XS Ineff= 2 , 0
          441.75 1631.89
Permanent Ineff=
       F       F
Bank Sta=470.9,485.9
XS Rating Curve= 0 ,0
Exp/Cntr=0.3,0.1

Type RM Length L Ch R = 1 ,12246   ,312.1,317.5,322.9
XS GIS Cut Line= 4
     1766351.626       96643.846     1766573.447       96491.741
     1766899.001       96403.753     1767277.347       96210.181
#Sta/Elev= 30
     6.1 1692.42    55.1 1676.81   100.2 1675.77     141 1688.28   171.8 1672.36
   189.9 1655.67   202.3 1655.55   214.6 1645.19   251.4 1630.84   285.4 1622.41
   443.1 1608.25   450.6 1608.15   458.1 1609.53   463.5 1610.11     474  1626.4
   494.9 1632.63   505.4 1646.88   547.3 1660.54   589.2 1684.28   667.3 1711.06
   701.4 1731.67   724.1 1735.92   769.6 1768.92     815 1782.26   826.4 1795.71
   860.5 1812.58   914.2 1830.83   958.6 1832.48   980.8 1843.79  1031.2 1852.08
#Mann= 3 , 0 , 0
       0     .08       0   443.1    .045       0   458.1     .08       0
Bank Sta=443.1,458.1
XS Rating Curve= 0 ,0
Exp/Cntr=0.3,0.1

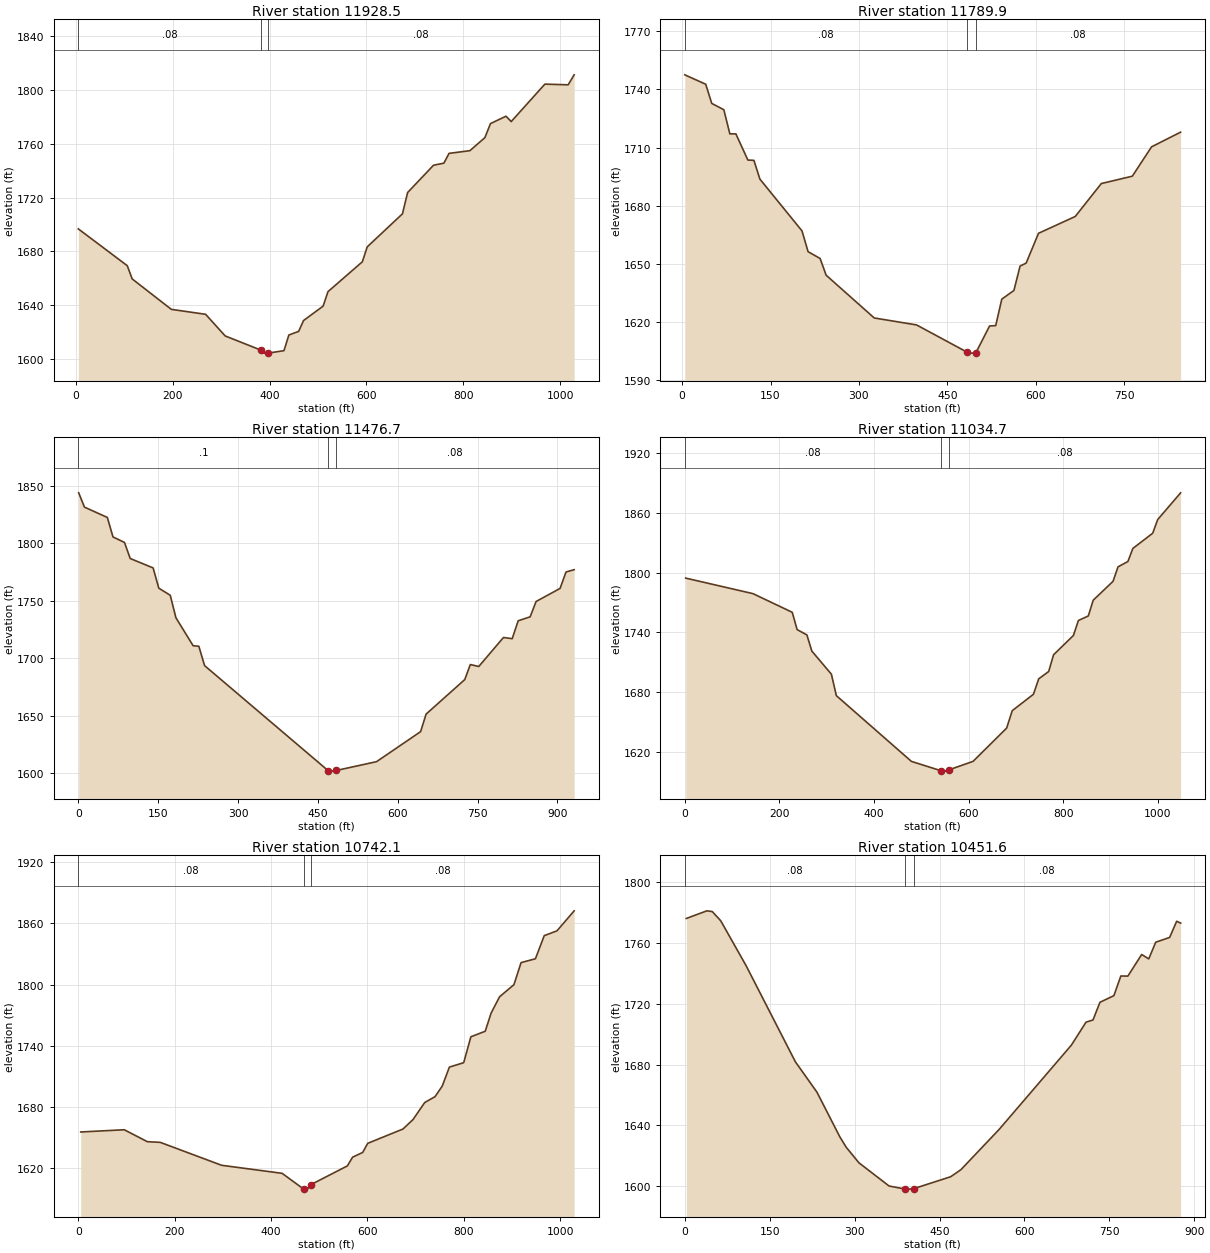
Type RM Length L Ch R = 1 ,11928.5 ,133.5,138.6,143.7
XS GIS Cut Line= 4
     1766362.058       96762.552     1766630.639       96764.502
     1767000.186       96755.703     1767369.734       96628.122
#Sta/Elev= 30
     4.7 1696.71   105.8 1669.37     116 1659.51   196.9 1636.89   267.7 1633.22
   308.2 1617.12   381.6 1606.65   389.1 1604.36   396.6 1604.37   429.6 1606.18
   439.7 1617.82   459.9 1620.51     470 1628.56   510.5 1639.31   520.6 1650.08
   591.5 1672.23   601.6 1683.33   674.4  1707.9   685.1 1723.73   738.6 1744.03
     760 1745.56   770.7 1752.85   813.8 1754.85   844.8 1764.57   856.3 1774.98
   888.4 1780.47   899.1 1776.46   968.7 1804.32  1016.8  1803.8  1029.2 1811.23
#Mann= 3 , 0 , 0
     4.7     .08       0   381.6    .045       0   396.6     .08       0
Bank Sta=381.6,396.6
XS Rating Curve= 0 ,0
Exp/Cntr=0.3,0.1

Type RM Length L Ch R = 1 ,11789.9 ,313.2,313.2,313.2
XS GIS Cut Line= 4
     1766266.291       96824.021     1766639.068       96874.526
     1766850.709       96917.816     1767091.209       96997.181
#Sta/Elev= 30
     4.6 1747.52    40.1 1742.67    50.3 1732.78    70.8 1729.53      81 1717.08
    91.2 1717.08   111.6 1703.57   121.8 1703.42     132 1693.74   203.4 1667.02
   213.7 1656.32   234.1 1652.81   244.3 1644.19   325.9 1622.13   397.6 1618.55
   483.1 1604.54   490.6    1604   498.1  1604.1   521.5    1618   531.9 1618.19
   542.2 1631.83   562.8 1636.31   573.2 1648.89   583.5 1650.43   604.5  1665.8
   666.8 1674.47     711 1691.45   763.6 1695.25   796.2 1710.38   845.5 1717.96
#Mann= 3 , 0 , 0
     4.6     .08       0   483.1    .045       0   498.1     .08       0
Bank Sta=483.1,498.1
XS Rating Curve= 0 ,0
Exp/Cntr=0.3,0.1

Type RM Length L Ch R = 1 ,11476.7 ,459.1,441.9,424.7
XS GIS Cut Line= 4
     1766123.293       97226.085     1766405.782       97124.647
     1766829.063       97216.037     1767007.608       97302.492
#Sta/Elev= 30
      .7 1843.97    11.5 1831.51    54.5 1822.52    65.1 1805.56    86.7 1800.75
    97.5 1786.76   140.5 1778.57   151.2 1760.93   172.7 1754.73   183.4 1735.11
   215.7  1710.8   226.4 1710.33   237.2 1693.48     470 1601.73   477.5 1601.56
     485 1602.16   560.3 1609.79   643.1 1635.95   653.4 1651.21   726.1 1681.32
   736.5 1694.39   752.4 1692.71   798.8 1717.96   815.2 1716.92   826.4  1732.5
   848.9 1735.96   860.1 1749.33   905.1 1760.69   916.3 1775.01   931.6 1777.01
#Mann= 3 , 0 , 0
       0      .1       0     470    .045       0     485     .08       0
Bank Sta=470,485
XS Rating Curve= 0 ,0
Exp/Cntr=0.3,0.1

Type RM Length L Ch R = 1 ,11034.7 ,286,292.7,299.4
XS GIS Cut Line= 4
     1766225.896       97692.771     1766586.645       97613.582
     1766888.895       97429.598     1767202.558        97345.22
#Sta/Elev= 30
     1.9 1794.46   144.2 1778.88   227.1 1760.19   237.4 1742.85   258.1 1737.49
   268.5 1721.34   309.9 1698.11   320.3 1676.66     479 1610.72   542.5 1601.22
     550 1600.97   557.5 1602.12   609.3 1610.75   680.3 1644.12   692.1 1661.56
   736.9 1678.02   748.1 1693.51   769.1 1700.81   779.5 1717.64   821.4 1736.95
   831.9 1751.97   852.9 1756.55   863.3 1772.32   905.2 1791.29   915.7 1805.74
   936.6 1811.14   947.1 1824.23     989 1839.46   999.5 1853.12    1048 1879.96
#Mann= 3 , 0 , 0
       0     .08       0   542.5    .045       0   557.5     .08       0
Bank Sta=542.5,557.5
XS Rating Curve= 0 ,0
Exp/Cntr=0.3,0.1

Type RM Length L Ch R = 1 ,10742.1 ,295.2,290.5,285.8
XS GIS Cut Line= 4
     1766471.679       98030.318     1766639.438        97837.95
     1767074.976       97723.566     1767312.542       97503.597
#Sta/Elev= 30
       5 1655.46    95.4 1657.64   143.3 1645.94   170.1 1645.28   297.5 1622.81
     423 1614.93   467.8 1599.49   475.3 1599.44   482.8 1603.83   558.5 1622.21
   569.4 1630.78   590.3  1635.4   600.8 1644.34     674 1658.38   694.9 1667.69
   719.1 1684.35   740.5  1690.1   755.4  1700.4   770.3 1719.06     800 1723.39
   814.9 1748.77   844.7 1754.22   856.9 1772.03   874.5    1788   904.3 1799.88
   919.1 1821.48   948.9 1825.26   967.2 1847.92   993.6 1852.63  1029.3 1872.26
#Mann= 3 , 0 , 0
       0     .08       0   467.8    .045       0   482.8     .08       0
Bank Sta=467.8,482.8
XS Rating Curve= 0 ,0
Exp/Cntr=0.3,0.1

Type RM Length L Ch R = 1 ,10451.6 ,187.3,171.1,154.8
XS GIS Cut Line= 4
     1766586.645       98308.683     1766745.023       98137.107
     1767096.973       97965.532     1767303.106       97822.437
#Sta/Elev= 30
     2.7 1776.19      39 1781.22    48.6 1780.71    63.5 1774.67   108.3 1745.11
   195.4  1681.8   233.5  1661.8     274 1632.33   285.2 1625.52   307.8 1615.24
   360.9 1600.02   389.5 1597.99     397 1597.96   404.5 1598.28   469.7 1606.11
   487.9 1610.79   555.4 1637.29     683 1692.78   708.9 1707.92   721.2 1709.34
   733.5    1721   758.1 1725.36   770.4 1738.31   782.8 1738.23   807.2 1752.46
   819.7 1749.58     832 1760.55   856.6 1763.69     869 1774.34     876 1773.15
#Mann= 3 , 0 , 0
       0     .08       0   389.5    .045       0   404.5     .08       0
Bank Sta=389.5,404.5
XS Rating Curve= 0 ,0
Exp/Cntr=0.3,0.1