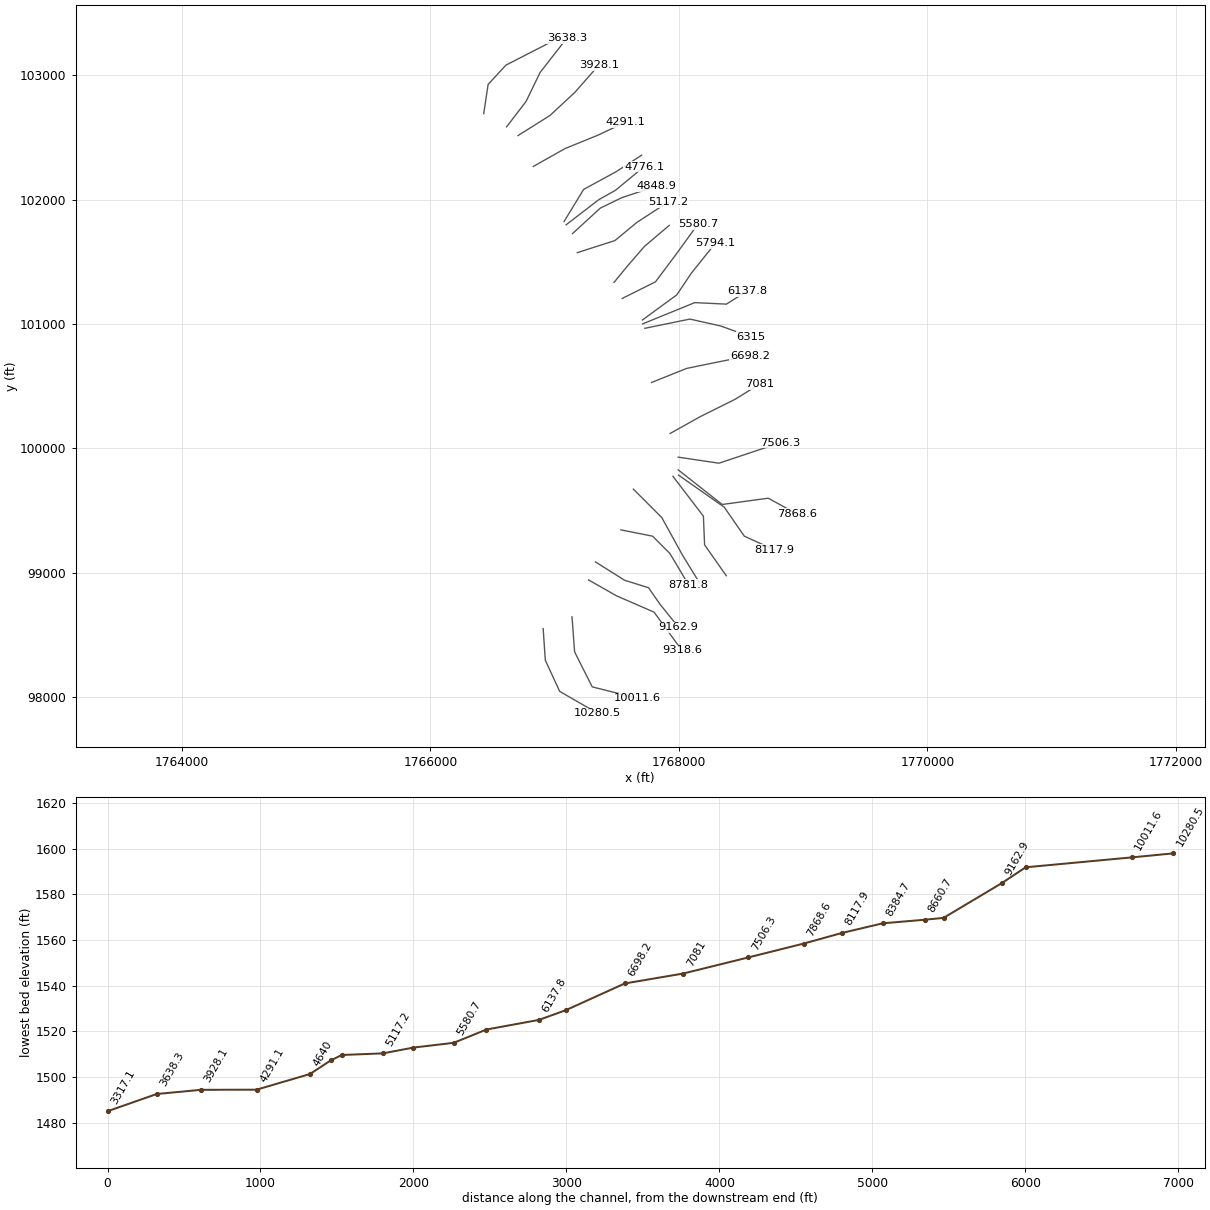
HEC-RAS study War Creek.prj: War Creek

--- War Creek.g01 (geometry) --- (continued)

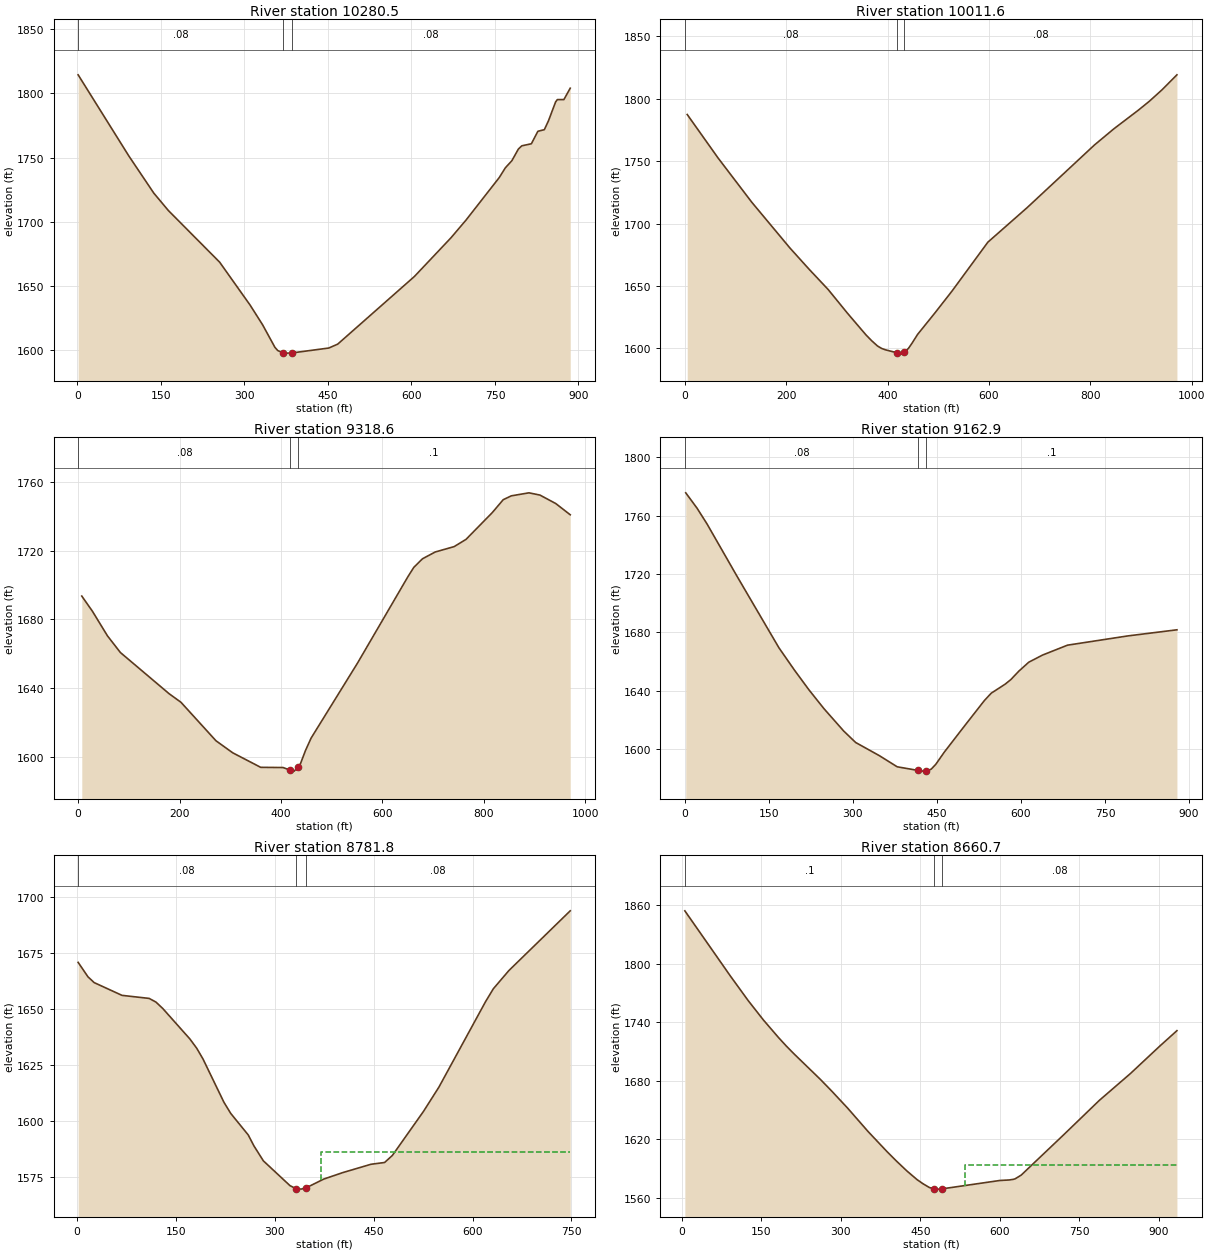
Type RM Length L Ch R = 1 ,10280.5 ,268.1,268.9,269.8
XS GIS Cut Line= 4
     1766907.799       98550.649     1766925.264       98295.886
     1767040.704       98045.765     1767347.737       97868.745
#Sta/Elev= 30
     1.2 1814.51    92.4 1751.28   137.2  1722.4   163.4 1708.85   255.4 1668.71
   310.3 1635.19   332.5 1620.02   354.8 1602.36   359.9 1599.89   369.6  1598.1
   377.1 1597.92   384.6 1598.02   451.4 1601.89   467.4 1604.89   605.2 1657.54
   671.1 1687.74     698 1701.46   757.7 1734.56   768.7 1742.17   780.4  1747.7
     792  1756.7   798.2 1759.26   815.4 1760.86   827.1 1770.57   838.7 1771.83
   846.1 1778.71   858.9  1793.4   862.1 1795.25   873.8 1795.25   885.2  1804.1
#Mann= 3 , 0 , 0
     1.2     .08       0   369.6    .045       0   384.6     .08       0
Bank Sta=369.6,384.6
XS Rating Curve= 0 ,0
Exp/Cntr=0.3,0.1

Type RM Length L Ch R = 1 ,10011.6 ,677.2,692.9,708.7
XS GIS Cut Line= 4
     1767139.988       98645.164     1767160.954       98363.226
      1767302.85        98081.84     1767664.796       97991.147
#Sta/Elev= 30
     4.7 1787.42    65.5 1752.62   132.3    1717   207.5 1680.37   245.6 1663.23
   282.7 1647.21   320.9 1628.16   357.3 1610.83   368.7 1606.09     380 1601.94
   383.4 1601.08   388.7 1599.86   396.2 1598.78   417.8 1596.54   425.3 1596.17
   432.8 1597.31   436.6 1597.99   441.4 1600.09     448 1603.95   459.3 1611.19
   493.3 1628.29   527.3 1645.97   597.9 1685.08   675.6 1712.84   808.2 1762.98
   846.6 1775.97   894.6 1790.81   916.6 1798.05   941.4 1807.15     971 1819.23
#Mann= 3 , 0 , 0
       0     .08       0   417.8    .045       0   432.8     .08       0
Bank Sta=417.8,432.8
XS Rating Curve= 0 ,0
Exp/Cntr=0.3,0.1

Type RM Length L Ch R = 1 ,9318.6  ,153.3,155.7,158.2
XS GIS Cut Line= 4
     1767272.948       98942.193     1767497.316       98814.611
     1767800.873        98682.63     1768025.241       98374.674
#Sta/Elev= 30
     7.2 1693.57    28.1 1684.79    57.8 1670.46    83.3 1660.77   179.3 1636.84
   202.6 1631.88   271.7 1609.49   304.8 1602.48   359.9 1594.04     404 1593.93
   418.6 1592.33   426.1 1591.84   433.6 1594.47   438.3 1596.16   448.1 1603.76
   459.2 1611.01     551 1654.75   649.8 1704.68   661.6 1710.21   678.8 1715.24
   703.8 1719.18   741.3 1722.33   764.7 1726.54   816.2 1742.01     838 1749.59
     854 1751.83   888.7 1753.58   910.4 1752.27   941.6 1747.35   970.1 1740.83
#Mann= 3 , 0 , 0
       0     .08       0   418.6    .045       0   433.6      .1       0
Bank Sta=418.6,433.6
XS Rating Curve= 0 ,0
Exp/Cntr=0.3,0.1

Type RM Length L Ch R = 1 ,9162.9  ,392.1,381.1,370.1
XS GIS Cut Line= 5
     1767329.476       99086.418     1767562.806       98939.583
     1767755.792       98879.431      1767847.48       98747.446
     1767998.042       98560.834
#Sta/Elev= 30
     1.6 1775.75    21.8 1765.22    39.5 1754.49    93.5  1718.3     168 1669.45
   195.7 1654.15   221.5 1640.67   248.4  1627.7   283.7 1612.35   304.9 1604.55
   347.3  1595.5     379 1587.89   416.2 1585.39   423.7 1584.92   431.2 1584.93
   439.8  1586.3   447.9  1589.6   463.3 1598.06     502  1617.3   534.7 1633.34
     543 1636.78     547  1638.4   571.7 1644.55   581.7 1647.63   596.2  1653.5
   613.9 1659.62   638.5 1664.51     683 1671.29   790.9 1677.65   878.3 1681.82
#Mann= 3 , 0 , 0
       0     .08       0   416.2    .045       0   431.2      .1       0
Bank Sta=416.2,431.2
XS Rating Curve= 0 ,0
Exp/Cntr=0.3,0.1

Type RM Length L Ch R = 1 ,8781.8  ,127.4,121.1,114.7
XS GIS Cut Line= 4
     1767533.731        99344.47     1767788.662       99293.964
     1767928.152       99154.474     1768077.263       98904.353
#Sta/Elev= 30
     1.9 1670.97    16.8 1664.52    26.2 1661.93    68.4 1656.23   109.6 1654.87
   119.9 1653.23   130.2 1650.38   171.5 1636.71   181.8 1632.58   191.3 1627.78
     223 1608.48   233.3 1603.51   259.9 1593.87   268.5 1588.99   282.8 1582.32
   323.2 1571.23   332.5 1569.87     340 1569.68   347.5 1570.24   374.5 1574.18
   403.1 1577.05     446 1580.78   466.7 1581.58   478.5 1584.74   525.6 1604.38
     549 1615.22   619.8 1653.43   631.6 1659.18   655.1 1667.29   748.2 1693.99
#Mann= 3 , 0 , 0
     1.9     .08       0   332.5    .045       0   347.5     .08       0
#XS Ineff= 2 , 0
                          370.38         1586.32
Permanent Ineff=
       F       F
Bank Sta=332.5,347.5
XS Rating Curve= 0 ,0
Exp/Cntr=0.3,0.1

Type RM Length L Ch R = 1 ,8660.7  ,286.8,276,265.3
XS GIS Cut Line= 4
     1767633.696       99672.489     1767862.464       99443.722
      1768031.13       99138.375     1768168.198        98915.62
#Sta/Elev= 30
     5.5  1854.3    91.3 1787.53   125.1 1762.17   153.7 1742.36   182.3  1724.3
   196.6 1715.82     211 1707.86   261.3 1681.37   282.5  1669.5   312.4  1652.1
   351.3 1627.91   386.6 1607.55     404 1598.04   424.3 1587.59   443.8 1578.55
   455.3 1574.24   466.9 1570.52   476.3 1569.03   483.8 1568.88   491.3  1569.2
   599.4 1577.72   617.8 1578.29   625.3 1578.93   628.7 1579.47   640.1 1583.26
   719.8  1624.4   787.6 1659.94   846.4 1687.53   900.6 1715.09   933.9 1731.39
#Mann= 3 , 0 , 0
     5.5      .1       0   476.3    .045       0   491.3     .08       0
#XS Ineff= 2 , 0
                          534.11          1593.9
Permanent Ineff=
       F       F
Bank Sta=476.3,491.3
XS Rating Curve= 0 ,0
Exp/Cntr=0.3,0.1

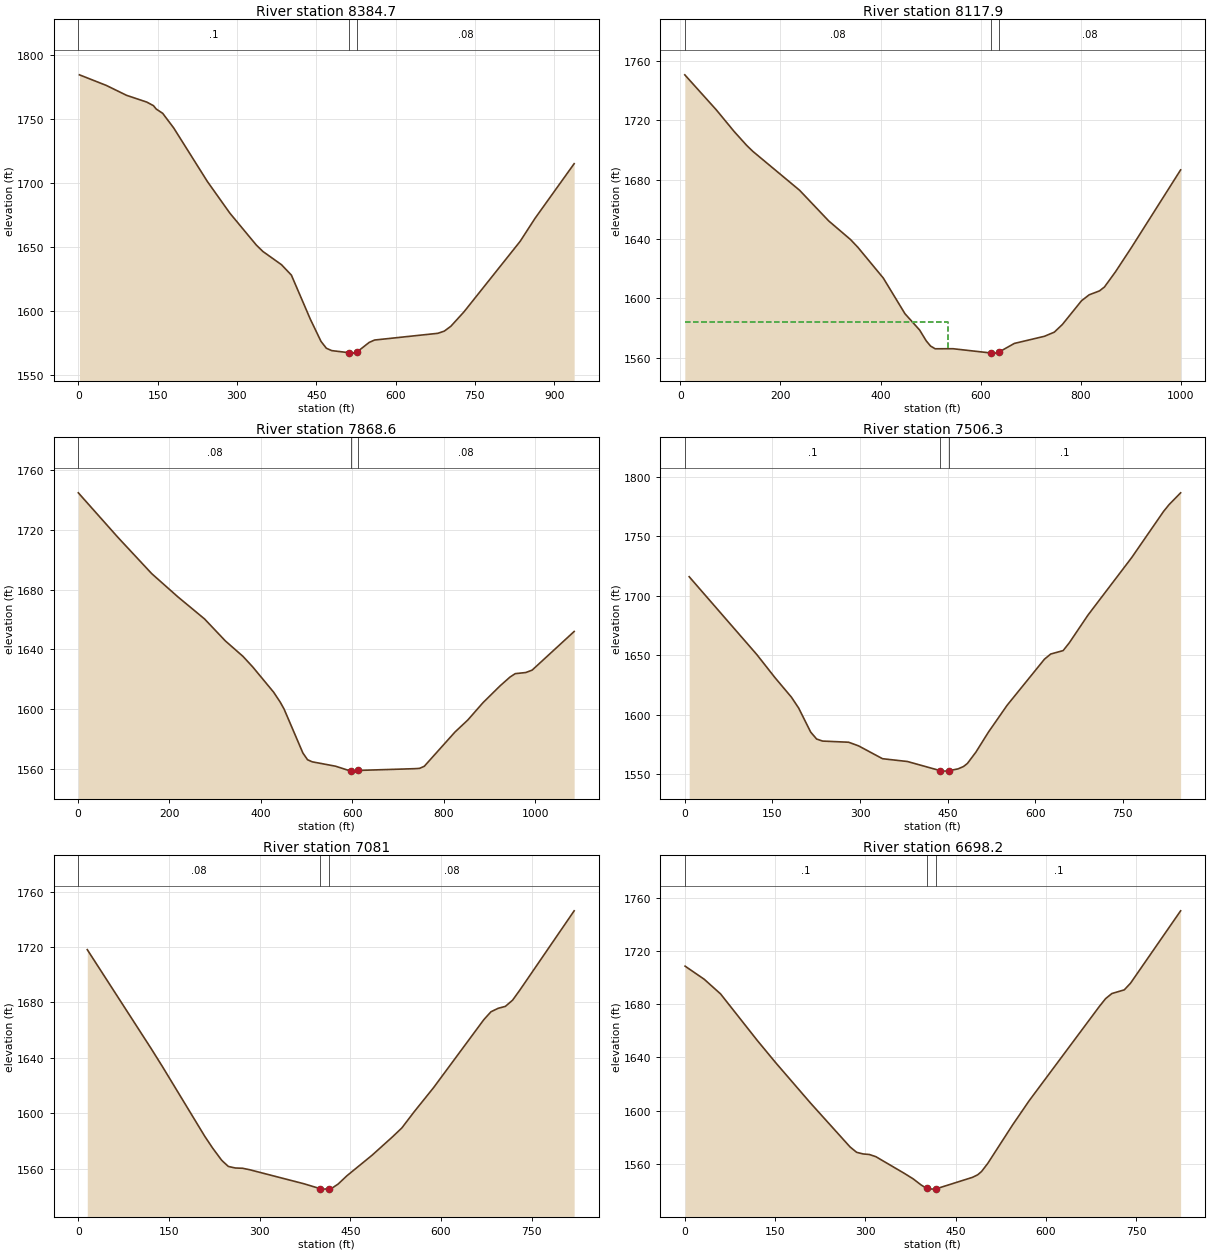
Type RM Length L Ch R = 1 ,8384.7  ,253.5,266.7,280
XS GIS Cut Line= 4
     1767952.513       99775.065     1768197.513         99455.1
     1768207.133       99224.219     1768381.705       98975.695
#Sta/Elev= 30
     2.1 1784.67      53 1776.38    91.3 1768.65   129.5 1763.38   142.2 1760.55
   147.1 1758.02   159.6 1754.58   180.4 1743.17   244.1 1701.34   286.6 1676.63
   336.6 1651.74   349.1  1646.7   384.3 1636.35     403 1628.22   438.7  1593.9
     459 1576.47   469.1 1571.12   479.2 1569.27   512.2 1567.62   519.7  1567.3
   527.2 1568.23   550.1 1575.67   560.2 1577.52   679.9 1582.77   692.2 1584.49
   704.6 1588.29   729.3 1599.48   835.6 1654.59   863.8 1672.58   937.8 1715.26
#Mann= 3 , 0 , 0
       0      .1       0   512.2    .045       0   527.2     .08       0
Bank Sta=512.2,527.2
XS Rating Curve= 0 ,0
Exp/Cntr=0.3,0.1

Type RM Length L Ch R = 1 ,8117.9  ,222.3,249.3,275.7
XS GIS Cut Line= 4
     1767997.897       99784.586     1768365.548       99527.026
     1768526.999       99293.964     1768769.905       99183.334
#Sta/Elev= 30
     9.2 1750.66    72.4 1726.94   107.6 1712.51   132.7 1703.12     145  1699.1
   238.5 1672.83   296.6 1652.18   340.2 1639.61   354.7 1634.45   405.6 1613.67
   448.9 1589.61   478.2 1578.62   491.4 1571.31     500 1567.84   509.2 1566.01
   544.7 1566.05   621.6 1563.13   629.1 1563.08   636.6  1563.8   667.2 1569.61
   727.5 1574.44   747.1 1577.23   763.2 1582.39   801.4 1598.39   816.7 1602.39
   837.3 1605.03   847.2 1607.66   869.1 1617.83   900.7 1634.06   999.3 1686.58
#Mann= 3 , 0 , 0
     9.2     .08       0   621.6    .045       0   636.6     .08       0
#XS Ineff= 2 , 0
          534.86 1583.82
Permanent Ineff=
       F       F
Bank Sta=621.6,636.6
XS Rating Curve= 0 ,0
Exp/Cntr=0.3,0.1

Type RM Length L Ch R = 1 ,7868.6  ,357.9,362.3,366.6
XS GIS Cut Line= 4
     1767994.717       99827.243     1768349.029       99548.895
     1768719.399       99599.403     1768947.876        99474.34
#Sta/Elev= 30
      .7 1744.96    87.1 1715.17   161.2 1690.79   218.1 1675.31   276.5 1660.48
   322.3 1645.67   360.9 1635.29   381.9 1628.31   427.7 1611.36   442.2 1604.65
   450.6 1600.01   491.7 1570.58   501.9 1566.06   512.1 1564.68   563.1 1561.74
   596.5 1558.45     604 1558.44   611.5 1558.89   736.7 1560.09   746.9  1560.3
   757.1 1561.68   824.4  1584.7   852.2 1592.68   885.5 1604.32   922.8 1615.58
   944.4 1621.45     956 1623.77     979 1624.52   992.9 1626.13  1084.8 1652.03
#Mann= 3 , 0 , 0
      .7     .08       0   596.5    .045       0   611.5     .08       0
Bank Sta=596.5,611.5
XS Rating Curve= 0 ,0
Exp/Cntr=0.3,0.1

Type RM Length L Ch R = 1 ,7506.3  ,422.4,425.4,428.4
XS GIS Cut Line= 3
     1767994.548       99929.501     1768322.574       99880.786
     1768813.195      100044.327
#Sta/Elev= 30
     7.5 1716.01   123.5 1650.37   154.1 1631.23   182.6 1614.57     195 1605.39
   215.5 1585.22   225.7 1579.37   235.9 1577.66   280.5 1576.68   297.3 1573.66
   338.5 1562.81   381.1 1560.46   437.6 1552.72   445.1 1552.36   452.6 1552.73
   467.8 1554.26   477.1 1556.24   483.8 1558.82   498.4 1568.39   519.7 1585.12
   551.7 1607.74   615.7  1646.6   626.4 1650.94   647.7 1653.83   658.3 1660.42
   690.3 1683.78     765 1732.09   819.6 1770.98   828.9 1776.63   848.8 1786.63
#Mann= 3 , 0 , 0
       0      .1       0   437.6    .045       0   452.6      .1       0
Bank Sta=437.6,452.6
XS Rating Curve= 0 ,0
Exp/Cntr=0.3,0.1

Type RM Length L Ch R = 1 ,7081    ,389,382.7,376.5
XS GIS Cut Line= 4
     1767930.287      100120.247     1768173.463      100255.968
     1768451.718      100394.233      1768648.55      100515.416
#Sta/Elev= 30
    14.8 1718.06   120.8 1646.49   139.3  1633.6   209.2  1583.4   222.3 1574.86
   236.6 1566.45   238.9 1565.39   248.2 1561.67   259.8 1560.55   271.4 1560.37
   282.8 1559.37   373.2 1549.19   399.6 1545.71   407.1 1545.31   414.6  1545.7
   419.4 1545.97   429.7 1548.92   444.3 1554.93   486.1 1569.81     520 1583.12
   535.2 1589.43   555.2 1600.88   587.8 1618.57   670.9 1667.58   682.7 1673.26
   694.6 1675.74   706.5 1677.14   718.4 1681.59   730.3 1688.78   820.3 1746.06
#Mann= 3 , 0 , 0
       0     .08       0   399.6    .045       0   414.6     .08       0
Bank Sta=399.6,414.6
XS Rating Curve= 0 ,0
Exp/Cntr=0.3,0.1

Type RM Length L Ch R = 1 ,6698.2  ,393.2,383.2,373.3
XS GIS Cut Line= 4
     1767780.718      100530.161     1768062.833      100643.174
     1768300.767       100692.09      1768572.74      100745.777
#Sta/Elev= 30
      .5 1708.72    32.3 1698.85    59.5 1687.81   120.4 1652.86   150.9 1636.16
   209.2 1605.57   274.7 1572.67   285.6 1568.64   296.5 1567.41   306.8 1567.01
   317.6 1565.35     365 1552.77   379.5 1548.68   392.4  1544.2   400.2 1541.95
     403 1541.66   410.5 1540.95     418 1541.22   478.1 1549.82   486.7 1551.71
   493.1 1554.18   503.4 1560.25   544.7 1589.21   572.4 1607.54   689.1 1678.49
   699.4 1684.32   709.7 1688.11   730.3 1690.87   740.6 1695.81     824 1750.35
#Mann= 3 , 0 , 0
       0      .1       0     403    .045       0     418      .1       0
Bank Sta=403,418
XS Rating Curve= 0 ,0
Exp/Cntr=0.3,0.1

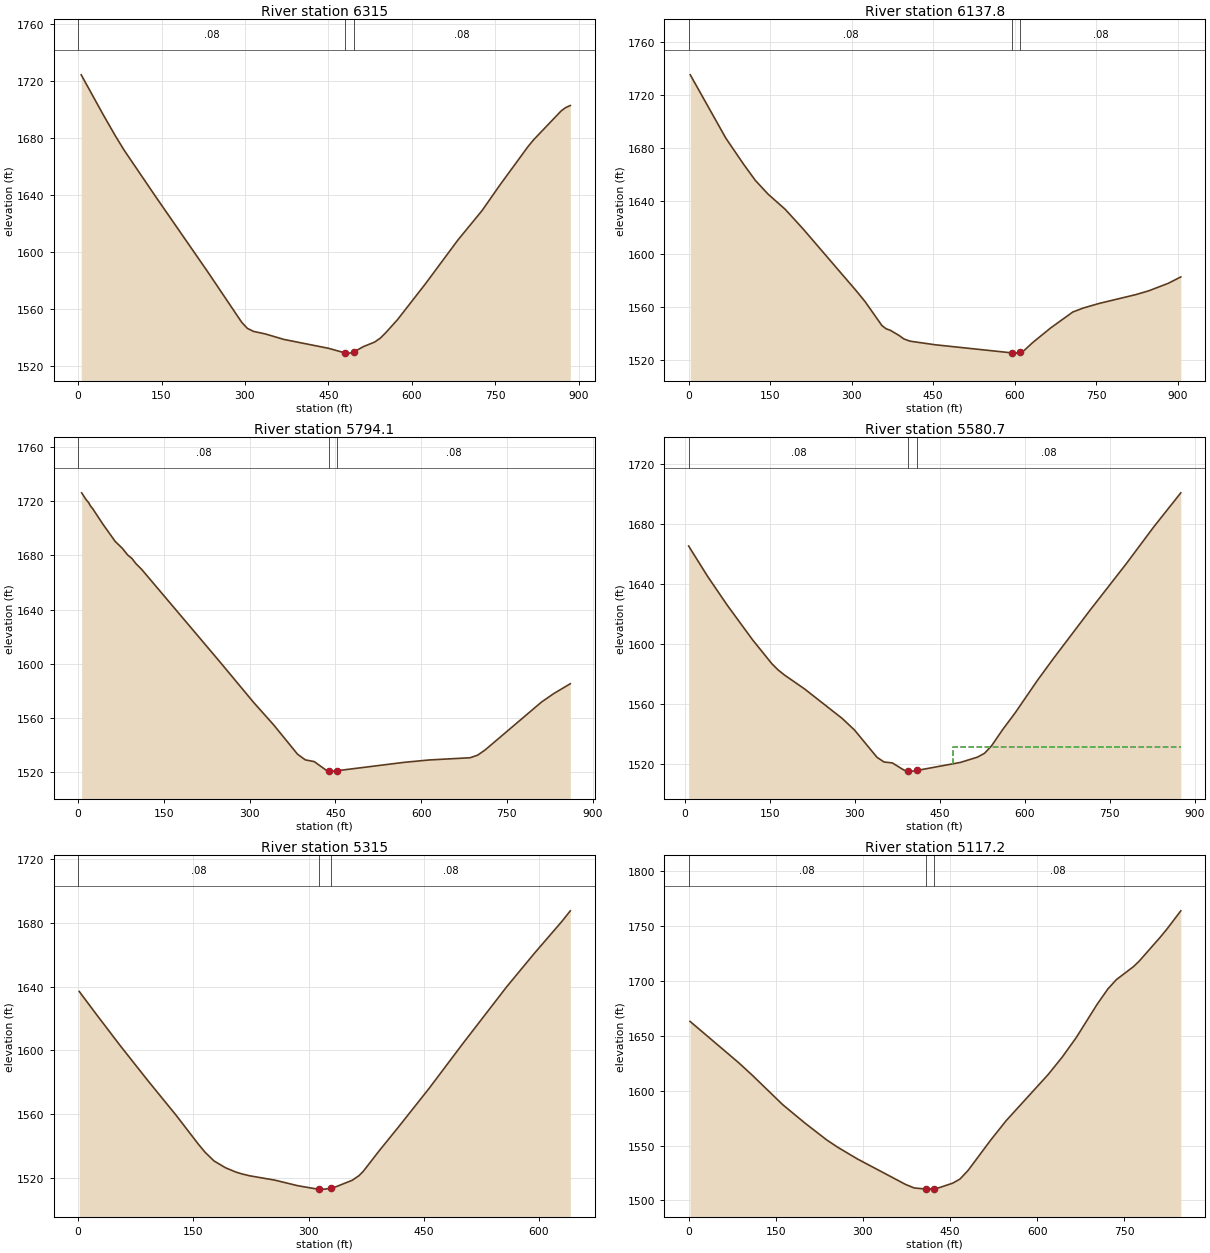
Type RM Length L Ch R = 1 ,6315    ,171,177.2,182.9
XS GIS Cut Line= 4
      1767726.58      100965.893     1768089.288         101040.
     1768337.644      100984.067     1768583.034      100896.115
#Sta/Elev= 30
     5.5 1724.45    44.8 1696.68    67.8 1681.09    82.9  1671.5     140 1638.73
     233 1586.36   291.4 1552.55   294.9  1550.6   304.3 1546.69   315.5 1544.54
   336.2 1542.81   370.2 1538.91   450.1 1532.71   480.5 1529.41     488 1529.31
   495.5 1530.03   513.4 1533.95     533 1537.01   543.4  1539.8   553.8 1543.86
   574.5 1552.82   624.8    1578   682.8  1608.5   726.3 1629.18     758 1646.86
   809.1 1674.14   819.8 1679.15   868.7 1699.13   876.6 1701.42   885.2 1702.94
#Mann= 3 , 0 , 0
       0     .08       0   480.5    .045       0   495.5     .08       0
Bank Sta=480.5,495.5
XS Rating Curve= 0 ,0
Exp/Cntr=0.3,0.1

Type RM Length L Ch R = 1 ,6137.8  ,321.6,343.7,366.3
XS GIS Cut Line= 4
     1767709.296       101001.52     1768127.768      101172.276
     1768382.699      101160.251     1768551.049      101266.071
#Sta/Elev= 30
       3  1735.1    68.5 1687.27   101.3 1667.52   122.8 1655.39   146.3 1645.01
   177.8 1633.55   210.6 1618.82   308.9 1571.88   324.8 1563.89   355.8 1545.82
   363.5 1543.38   371.3 1542.22   386.9 1538.46   396.3 1535.71   407.2 1534.06
   453.9  1531.3   595.4 1525.18   602.9    1525   610.4 1525.67     613 1525.82
   618.3 1527.25   633.2 1532.93   666.6 1544.07   707.2 1556.04   726.2 1559.01
   755.6  1562.5   823.1 1569.17     847 1572.04   882.8 1577.68     906 1582.54
#Mann= 3 , 0 , 0
       0     .08       0   595.4    .045       0   610.4     .08       0
Bank Sta=595.4,610.4
XS Rating Curve= 0 ,0
Exp/Cntr=0.3,0.1

Type RM Length L Ch R = 1 ,5794.1  ,208.5,213.4,214.2
XS GIS Cut Line= 4
      1767707.17      101032.861     1767983.467      101234.806
     1768101.313      101410.372     1768293.723       101649.75
#Sta/Elev= 30
     6.1 1726.25    14.3 1720.99    18.6 1718.88    21.5 1716.57    25.5 1714.52
    43.2 1703.18    64.9 1690.31    76.9 1685.47    86.7 1680.32    94.1 1677.78
   101.1 1673.94   111.2 1669.68   248.4 1601.22   306.7 1571.61   342.2 1554.81
   383.7 1533.27   397.3 1529.08   412.9 1527.82   433.9 1521.44   438.6 1521.08
   446.1 1520.77   453.6 1521.11   569.8 1527.24   614.4 1529.03   685.6 1530.65
   698.6 1532.54   711.6 1536.34   810.4 1571.77     832 1578.07   860.8  1585.3
#Mann= 3 , 0 , 0
       0     .08       0   438.6    .045       0   453.6     .08       0
Bank Sta=438.6,453.6
XS Rating Curve= 0 ,0
Exp/Cntr=0.3,0.1

Type RM Length L Ch R = 1 ,5580.7  ,273.9,265.7,261.6
XS GIS Cut Line= 4
     1767544.173      101205.966     1767812.175      101339.693
      1767974.44      101556.046     1768153.772      101803.857
#Sta/Elev= 30
     6.8 1665.44    40.7 1644.92    75.2 1625.77   119.8  1602.7   153.7 1586.78
     165 1582.53   176.3 1579.14     211 1570.04   278.1 1550.13   299.5 1542.51
   339.4  1524.2   351.8 1521.07   366.4 1520.46   385.5    1516     390  1515.2
   394.9  1515.1   402.4 1514.96   409.9 1515.41   486.7 1520.79   516.4 1524.27
   529.1 1526.84   541.7 1531.91   561.5 1542.86   583.2 1553.85   622.8 1575.72
     651  1590.3   714.8 1622.18   779.3 1653.51   827.7 1678.07   875.8 1701.01
#Mann= 3 , 0 , 0
     6.8     .08       0   394.9    .045       0   409.9     .08       0
#XS Ineff= 2 , 0
                          474.08         1531.31
Permanent Ineff=
       F       F
Bank Sta=394.9,409.9
XS Rating Curve= 0 ,0
Exp/Cntr=0.3,0.1

Type RM Length L Ch R = 1 ,5315    ,201.7,197.7,193.8
XS GIS Cut Line= 4
     1767478.238      101334.989     1767586.415      101466.683
     1767722.812      101624.244     1767922.703      101793.564
#Sta/Elev= 30
     1.4 1637.04    24.8 1621.96    55.6 1602.49    91.5  1580.6   127.5  1559.3
   156.2 1541.29   165.2 1536.05   176.9 1530.57   191.8 1526.29   205.2  1523.6
   213.6 1522.36   223.3 1521.23   255.9 1518.52   285.5 1515.05   306.8 1513.24
   313.7 1512.94   321.2 1512.85   328.7 1513.45   335.5  1514.3     357 1518.44
   365.8 1521.37   371.4 1524.13   391.2 1536.46   417.8 1552.31   457.4 1576.42
   500.5 1604.05     558 1639.99   593.8 1660.86   629.9 1681.07   640.8 1687.68
#Mann= 3 , 0 , 0
       0     .08       0   313.7    .045       0   328.7     .08       0
Bank Sta=313.7,328.7
XS Rating Curve= 0 ,0
Exp/Cntr=0.3,0.1

Type RM Length L Ch R = 1 ,5117.2  ,273.8,268.3,262.8
XS GIS Cut Line= 4
     1767182.691      101574.296     1767485.293      101671.278
     1767662.145      101817.619      1767913.63      101980.822
#Sta/Elev= 30
     2.4 1662.86    85.8 1625.43   109.8 1613.77   162.1 1587.04   200.5 1570.26
   237.2 1555.25   255.9 1548.64   290.3 1537.82   373.7 1514.51   388.1 1511.42
   407.7  1510.4   409.7 1510.33   422.7 1510.77   431.2 1511.63   454.5 1515.74
   467.1 1519.55   480.8 1527.23   520.2 1555.14   546.4 1572.52   618.9 1614.59
     643 1630.39   667.1 1648.13   703.3 1678.57   721.6 1692.37   736.3 1700.89
   765.5 1712.58   775.6 1717.73   811.8 1739.45   823.9 1747.25   847.1 1763.39
#Mann= 3 , 0 , 0
       0     .08       0   407.7    .045       0   422.7     .08       0
Bank Sta=407.7,422.7
XS Rating Curve= 0 ,0
Exp/Cntr=0.3,0.1

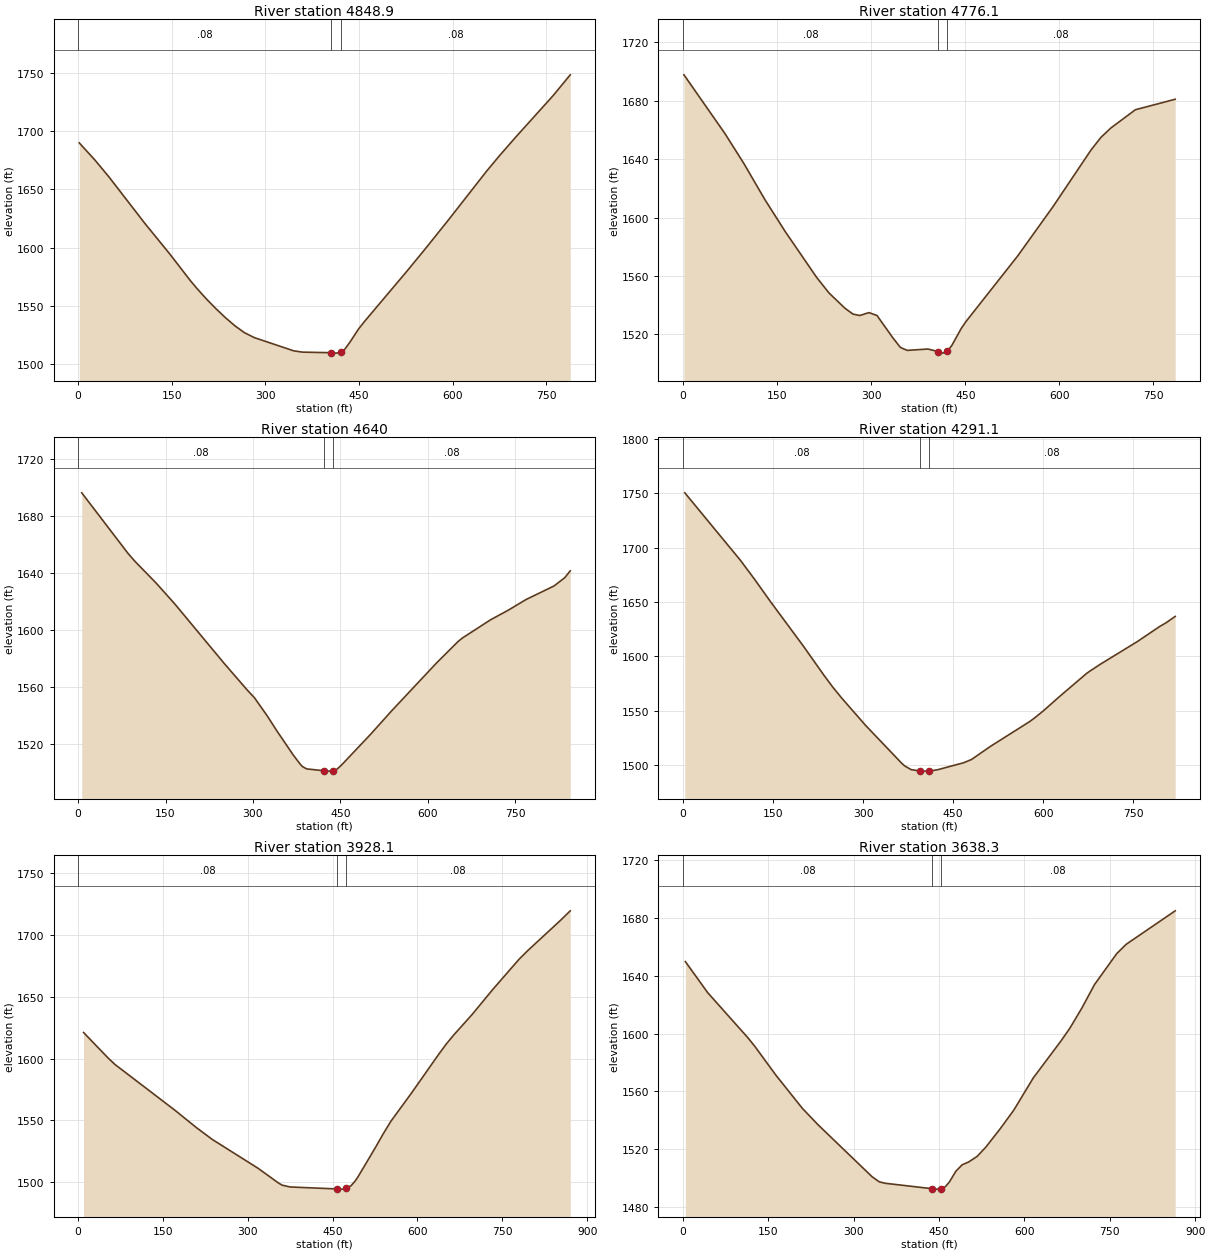
Type RM Length L Ch R = 1 ,4848.9  ,71.4,72.8,74.2
XS GIS Cut Line= 4
     1767144.302      101727.718      1767367.71      101932.313
     1767541.733      102016.973      1767819.23      102108.688
#Sta/Elev= 30
     1.8 1689.86    26.9 1675.16    49.6 1660.53   106.8 1620.93   146.7 1594.73
   180.1  1571.6   191.6 1564.32   206.6 1555.47   221.4 1547.43   236.5  1539.8
   251.5 1532.96   266.5 1527.16   282.5 1522.89   345.4  1511.6   359.7 1510.47
     406 1509.98   413.5 1509.62     421 1510.32   427.2 1512.79   436.2 1519.49
   449.6 1530.45   458.9 1536.72   527.9 1580.47     557 1599.46   594.2 1624.27
   654.5 1665.53   675.8 1679.17   701.6 1694.97     761 1730.22   788.7  1748.2
#Mann= 3 , 0 , 0
       0     .08       0     406    .045       0     421     .08       0
Bank Sta=406,421
XS Rating Curve= 0 ,0
Exp/Cntr=0.3,0.1

Type RM Length L Ch R = 1 ,4776.1  ,136.9,136.1,135.3
XS GIS Cut Line= 4
     1767092.565      101798.268     1767355.952      102000.511
     1767489.997      102075.764      1767720.46      102266.249
#Sta/Elev= 30
     1.4 1697.76    66.9 1657.46    96.6  1637.3   130.6 1612.24   163.1 1590.33
   212.9 1559.15   232.7 1548.41   258.2 1537.95   270.9 1533.97   281.8 1532.98
   296.4 1534.97   309.2 1533.01   334.5 1517.76   346.1 1511.38   349.1 1510.62
   357.7  1509.1   390.4 1510.05   406.5 1508.34     414 1507.23   421.5 1508.42
   428.9 1512.73   443.7 1524.19   451.2 1528.88   533.6 1573.75   590.2 1607.66
   650.7 1646.37   666.6 1655.03   682.4 1661.42   721.4 1673.88   784.8 1681.03
#Mann= 3 , 0 , 0
       0     .08       0   406.5    .045       0   421.5     .08       0
Bank Sta=406.5,421.5
XS Rating Curve= 0 ,0
Exp/Cntr=0.3,0.1

Type RM Length L Ch R = 1 ,4640    ,351,348.9,346.9
XS GIS Cut Line= 4
     1767075.943       101824.31     1767233.665      102082.819
     1767497.052      102226.271     1767700.134      102357.922
#Sta/Elev= 30
     6.2 1696.53    85.8 1653.93    97.7 1648.38   133.8 1633.25   165.5 1618.77
   250.3 1577.04   289.1  1558.7   302.7 1552.73     325 1539.79   340.8 1529.71
   369.8 1512.26   380.8 1506.39   384.7 1504.57   392.2 1502.84   421.9 1501.53
   429.4 1501.27   436.9  1501.4   444.4 1502.67   451.8 1505.42     502 1527.11
     538 1543.51   615.6 1577.34   652.2 1592.23   659.5 1594.64   707.5 1607.34
   738.4 1614.21   769.2 1621.75   816.7 1631.14   835.3    1637   844.7 1641.78
#Mann= 3 , 0 , 0
       0     .08       0   421.9    .045       0   436.9     .08       0
Bank Sta=421.9,436.9
XS Rating Curve= 0 ,0
Exp/Cntr=0.3,0.1

Type RM Length L Ch R = 1 ,4291.1  ,354.2,362.9,371.3
XS GIS Cut Line= 4
     1766829.479      102268.123      1767085.51      102412.052
     1767350.379       102519.72     1767567.924      102622.365
#Sta/Elev= 30
     2.9 1750.41    95.8 1688.18     119 1670.99   145.7 1650.32   200.2 1609.65
   234.9 1582.53   249.7 1571.55   264.6  1561.5     304 1536.61   364.2 1501.77
   369.5 1499.15   380.4 1495.74   394.8 1494.62   402.3 1494.42   409.8 1494.44
   424.1 1495.68   467.8 1502.15   480.7 1505.11   512.3  1517.2     577 1539.75
   584.2 1542.61   599.3 1549.31   627.1 1562.87   672.7 1584.36   677.6 1586.26
   695.5 1592.76   757.3 1613.65   794.3 1627.46   804.7 1630.76   820.2 1636.71
#Mann= 3 , 0 , 0
       0     .08       0   394.8    .045       0   409.8     .08       0
Bank Sta=394.8,409.8
XS Rating Curve= 0 ,0
Exp/Cntr=0.3,0.1

Type RM Length L Ch R = 1 ,3928.1  ,281.7,289.9,298.3
XS GIS Cut Line= 4
     1766705.915       102516.23     1766963.224      102677.791
     1767163.115      102863.572     1767357.009      103083.784
#Sta/Elev= 30
     9.6 1621.19    53.4 1600.33    65.3 1595.24     171 1558.29   208.6 1544.35
     237 1534.66   318.1 1511.25   353.2 1499.64   360.4 1497.62   374.7 1496.11
   457.8  1494.5   465.3 1494.36     470 1494.38   472.8 1494.94     482 1496.92
   489.2 1500.56     495 1504.46     525 1527.57     539 1538.81   552.8  1549.2
   589.4 1572.16   637.4 1603.46   650.9 1611.85   664.3 1619.27   696.9 1635.93
   732.7 1655.82   779.8  1680.6   795.1 1687.57     853 1712.07   870.1 1719.72
#Mann= 3 , 0 , 0
       0     .08       0   457.8    .045       0   472.8     .08       0
Bank Sta=457.8,472.8
XS Rating Curve= 0 ,0
Exp/Cntr=0.3,0.1

Type RM Length L Ch R = 1 ,3638.3  ,327.9,321.2,314.3
XS GIS Cut Line= 4
     1766613.537       102585.87     1766770.387      102790.671
     1766883.267      103023.486     1767097.586      103297.941
#Sta/Elev= 30
       4 1649.72    43.3 1628.24   114.1 1597.02   126.5 1590.95   162.7 1571.48
   209.6 1548.33   237.3 1536.95   332.2 1501.08   344.6  1497.6   354.9 1496.58
   438.2 1492.79   445.7 1492.52   453.2 1492.74   460.9 1494.16   468.3  1497.6
   479.5 1504.94   490.7 1509.37     502  1511.3   516.7  1515.1   532.1 1521.55
   557.3 1534.19   581.4 1547.18   615.4  1569.3   663.6 1594.58   679.8 1603.69
   701.4 1617.96     723 1633.78   762.2 1655.24   778.6 1661.61   864.9 1684.79
#Mann= 3 , 0 , 0
       0     .08       0   438.2    .045       0   453.2     .08       0
Bank Sta=438.2,453.2
XS Rating Curve= 0 ,0
Exp/Cntr=0.3,0.1

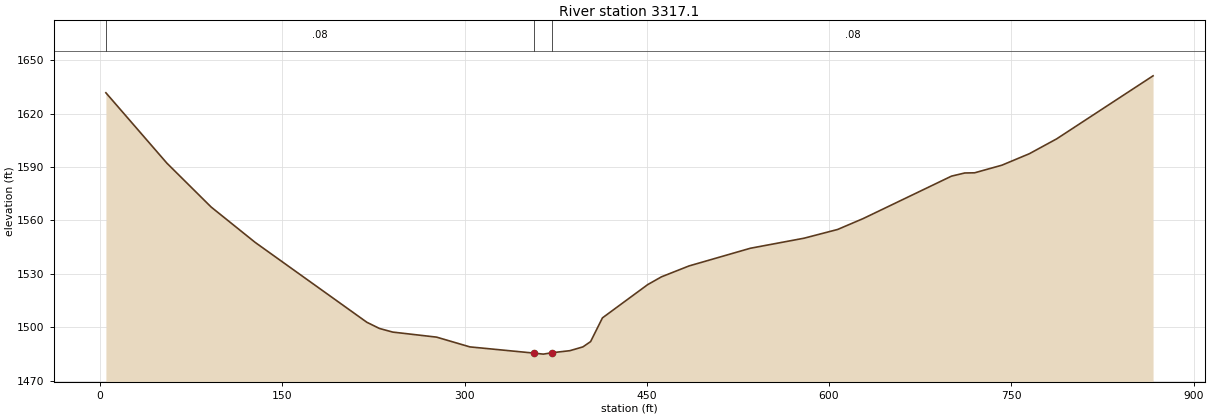
Type RM Length L Ch R = 1 ,3317.1  ,332.4,303.5,260.7
XS GIS Cut Line= 4
     1766429.395      102691.901      1766464.67      102927.067
     1766608.122      103082.277     1766979.685      103272.762
#Sta/Elev= 30
     4.8 1631.68      55 1592.18    91.4 1567.57   127.6 1547.73   219.6 1502.86
   229.9  1499.4   240.9 1497.35     277 1494.52   304.4 1489.04   357.3 1485.54
   364.8 1484.98   372.3 1485.79  386.69 1486.91  397.41 1489.04  403.75    1492
   413.5 1505.33   450.7 1523.98   462.1 1528.38   484.8 1534.49   535.2  1544.4
   579.5 1550.06   607.1 1554.96   628.2  1561.1   700.8 1584.89   711.7 1586.66
   719.8 1586.76   742.3 1591.04   764.9 1597.48   787.4 1605.83   866.7  1641.2
#Mann= 3 , 0 , 0
     4.8     .08       0   357.3    .045       0   372.3     .08       0
Bank Sta=357.3,372.3
XS Rating Curve= 0 ,0
Exp/Cntr=0.3,0.1