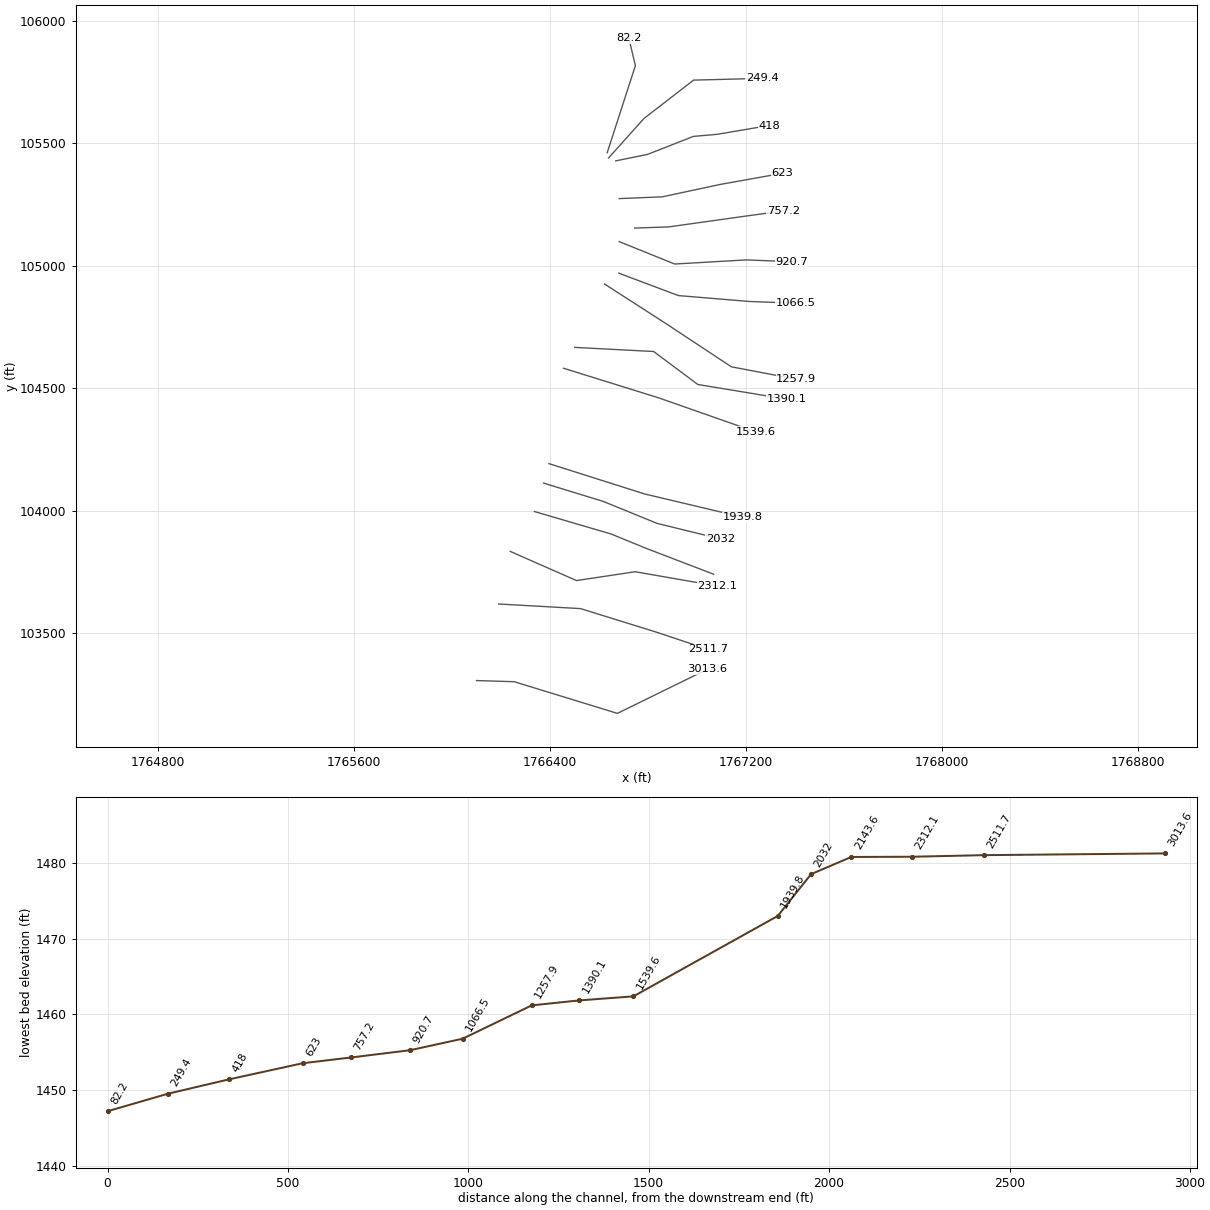
HEC-RAS study War Creek.prj: War Creek

--- War Creek.g01 (geometry) --- (continued)

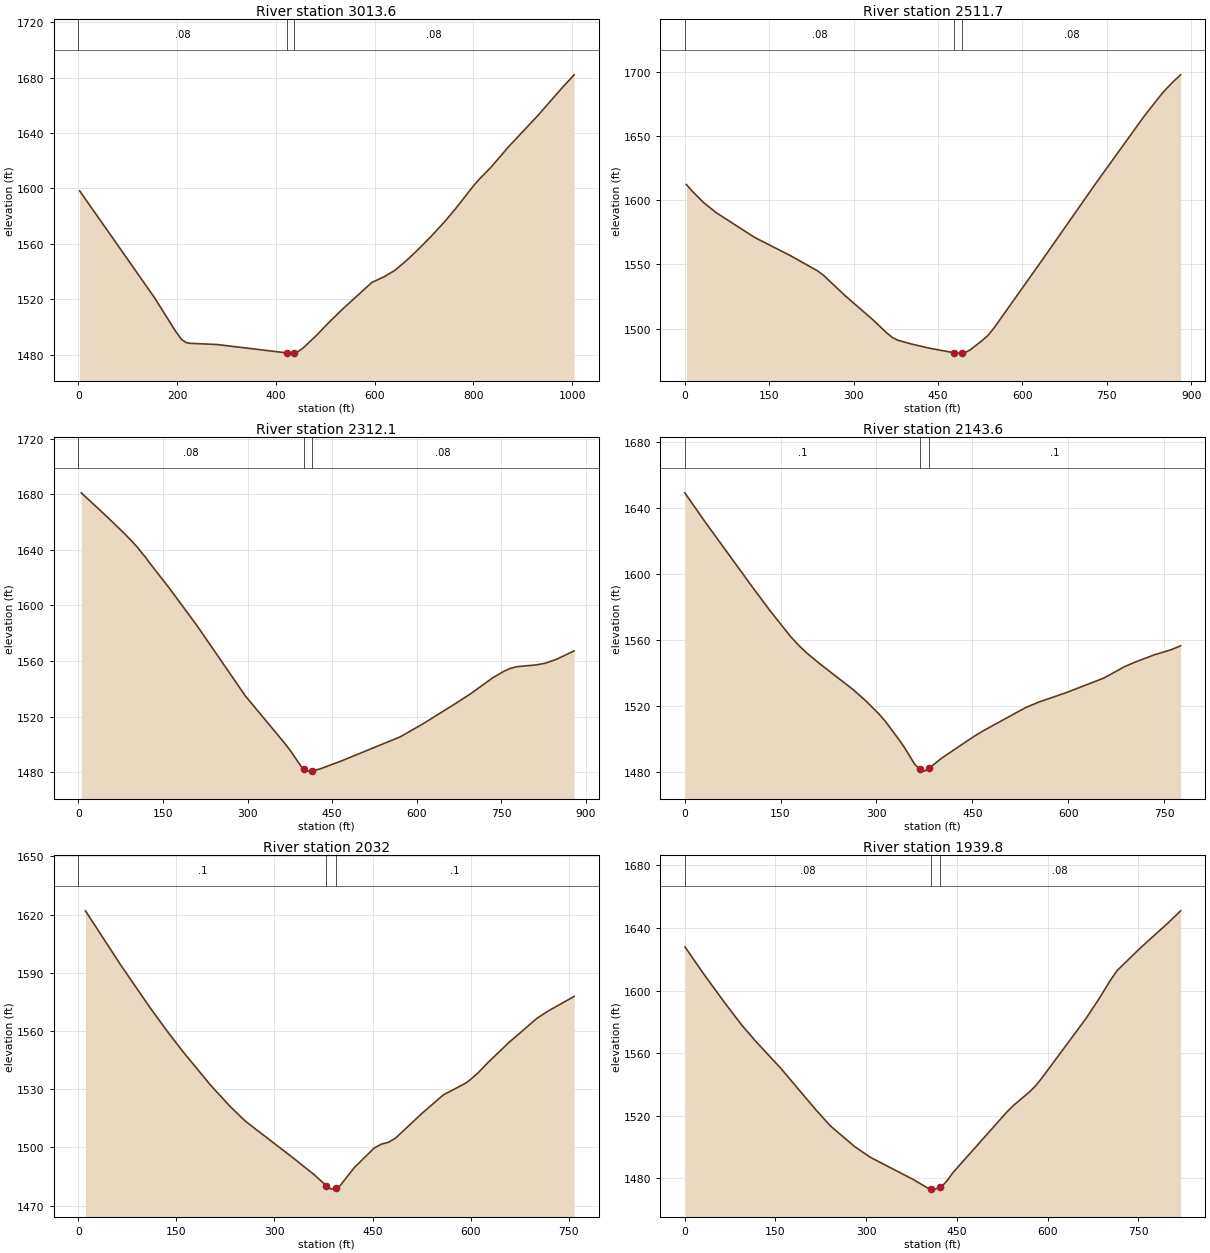
Type RM Length L Ch R = 1 ,3013.6  ,498.8,501.9,501.4
XS GIS Cut Line= 4
     1766101.191      103305.695     1766255.372      103300.982
      1766676.32      103171.641     1767044.119       103352.09
#Sta/Elev= 30
     2.6 1598.34   154.3 1521.25   196.7 1497.22   208.9 1491.21   217.9 1488.93
   225.1 1488.36   281.3 1487.45     422 1481.43   429.5 1481.25     437 1481.62
   443.7 1482.06   455.3 1484.96   482.4 1494.04   503.6 1501.97   535.3 1513.01
   594.6 1532.26   620.1 1536.47   641.6 1541.04   664.5 1547.98   688.9 1556.18
     713 1564.87   741.6 1575.91   764.2 1585.47   801.4 1602.37   813.1 1607.07
   835.7 1615.29   871.2    1630   930.5 1652.53   982.1 1673.51  1004.3 1681.99
#Mann= 3 , 0 , 0
       0     .08       0     422    .045       0     437     .08       0
Bank Sta=422,437
XS Rating Curve= 0 ,0
Exp/Cntr=0.3,0.1

Type RM Length L Ch R = 1 ,2511.7  ,189.2,199.6,210.1
XS GIS Cut Line= 4
     1766191.877      103618.457     1766525.814      103599.644
     1766836.234      103503.226     1767046.374      103433.124
#Sta/Elev= 30
     2.9 1612.12      13 1607.16    33.3 1598.18    55.4 1590.41   124.5 1570.92
   185.3 1557.42   235.9 1545.02   246.1 1541.71   284.3 1525.93   334.5 1506.85
   358.6 1496.84   369.1 1493.09   379.3 1490.96   403.5 1488.03   435.8 1484.74
   478.2 1481.35   485.7 1481.02   493.2 1481.08   500.5    1482   506.8 1483.48
     528 1490.68   538.6 1494.78   549.2 1500.44   637.9  1555.2   729.7 1612.73
     815 1664.59   842.9 1680.21     854 1685.91   868.4 1692.42     881 1697.51
#Mann= 3 , 0 , 0
       0     .08       0   478.2    .045       0   493.2     .08       0
Bank Sta=478.2,493.2
XS Rating Curve= 0 ,0
Exp/Cntr=0.3,0.1

Type RM Length L Ch R = 1 ,2312.1  ,180.7,168.5,156.3
XS GIS Cut Line= 4
     1766238.948      103833.315     1766509.433      103714.153
     1766748.879      103750.277     1767085.422        103691.5
#Sta/Elev= 30
     5.2 1680.94    51.2 1663.62    84.6 1650.52     104 1642.18   115.1 1636.43
   117.5 1635.52   122.8 1632.45   161.8  1612.1     210 1585.66   295.6 1535.15
   366.1  1500.7   376.3 1495.31     396  1483.6   399.5 1482.51     407 1480.81
   414.5 1481.09   427.5 1482.25   467.2 1488.27   570.8 1505.51   611.9 1515.07
   672.2 1530.34   696.4 1536.74   735.1 1548.06   755.6  1552.9   765.9 1554.69
   776.2 1555.85   812.2 1557.23   827.5 1558.38     848 1561.31   878.9 1567.26
#Mann= 3 , 0 , 0
       0     .08       0   399.5    .045       0   414.5     .08       0
Bank Sta=399.5,414.5
XS Rating Curve= 0 ,0
Exp/Cntr=0.3,0.1

Type RM Length L Ch R = 1 ,2143.6  ,111.5,111.5,111.5
XS GIS Cut Line= 4
      1766337.68      103996.191     1766650.452      103904.476
     1766793.904      103845.684     1767069.059       103740.14
#Sta/Elev= 30
      .3 1649.38    30.3 1632.73   106.7 1591.94   133.2 1578.19   165.8 1562.27
   177.9 1557.21   190.3 1552.61   209.5  1546.4   263.6 1530.15   283.3 1523.39
   304.3 1515.28   314.9 1510.49   336.8 1499.02   344.2 1494.86   359.7 1484.99
   367.7 1482.03   375.2 1480.78   382.7 1482.58   401.9 1488.61   450.7 1501.36
   467.5 1505.31   532.7 1519.16   554.2 1522.66   597.7 1528.46   656.1 1537.24
   687.4 1543.94   703.1  1546.6   734.4 1551.22   760.2 1554.24   775.7 1556.69
#Mann= 3 , 0 , 0
      .3      .1       0   367.7    .045       0   382.7      .1       0
Bank Sta=367.7,382.7
XS Rating Curve= 0 ,0
Exp/Cntr=0.3,0.1

Type RM Length L Ch R = 1 ,2032    ,90.4,92.3,95.6
XS GIS Cut Line= 4
     1766375.307      104112.307      1766619.88      104037.054
     1766838.585      103947.691     1767097.269      103884.196
#Sta/Elev= 30
    10.9 1621.91    65.1 1593.85   110.1 1571.81   138.4 1558.78   160.4 1549.19
   202.7  1531.9   232.4 1521.03   255.6 1513.48   329.5 1494.34   360.5 1486.01
   379.2 1480.33   386.7 1478.51   394.2 1479.32   397.7 1479.41   399.3 1479.89
   422.6  1489.8   452.3 1499.62   463.2 1501.67   474.2 1502.62   485.1 1504.79
   525.9 1517.65   558.3 1527.09   589.6  1532.6   598.1 1534.51   611.9  1538.6
   626.2 1543.65   658.5 1554.06   701.5 1566.53   718.2 1570.22   758.3  1577.8
#Mann= 3 , 0 , 0
       0      .1       0   379.2    .045       0   394.2      .1       0
Bank Sta=379.2,394.2
XS Rating Curve= 0 ,0
Exp/Cntr=0.3,0.1

Type RM Length L Ch R = 1 ,1939.8  ,400.1,400.2,397.9
XS GIS Cut Line= 3
     1766396.765      104191.903     1766788.071      104067.823
     1767186.699      103973.296
#Sta/Elev= 30
      .3 1627.88      31 1610.73    65.4 1592.51    94.4 1577.79   117.1 1567.65
   159.5 1549.95   216.3 1523.95   240.5 1513.55   280.8 1500.25   306.3 1493.48
   377.5 1479.22   401.7 1473.74   406.6 1473.23   414.1 1472.99   421.6 1474.24
   426.5 1475.24   434.8 1478.84   443.3 1483.41   532.5 1522.21   544.1 1526.65
     570 1535.09   580.4 1539.12   590.8  1544.1   663.6 1582.07   684.4 1594.24
   705.2 1607.25   715.6 1612.92   754.2 1627.43   798.8    1643   820.2 1650.95
#Mann= 3 , 0 , 0
       0     .08       0   406.6    .045       0   421.6     .08       0
Bank Sta=406.6,421.6
XS Rating Curve= 0 ,0
Exp/Cntr=0.3,0.1

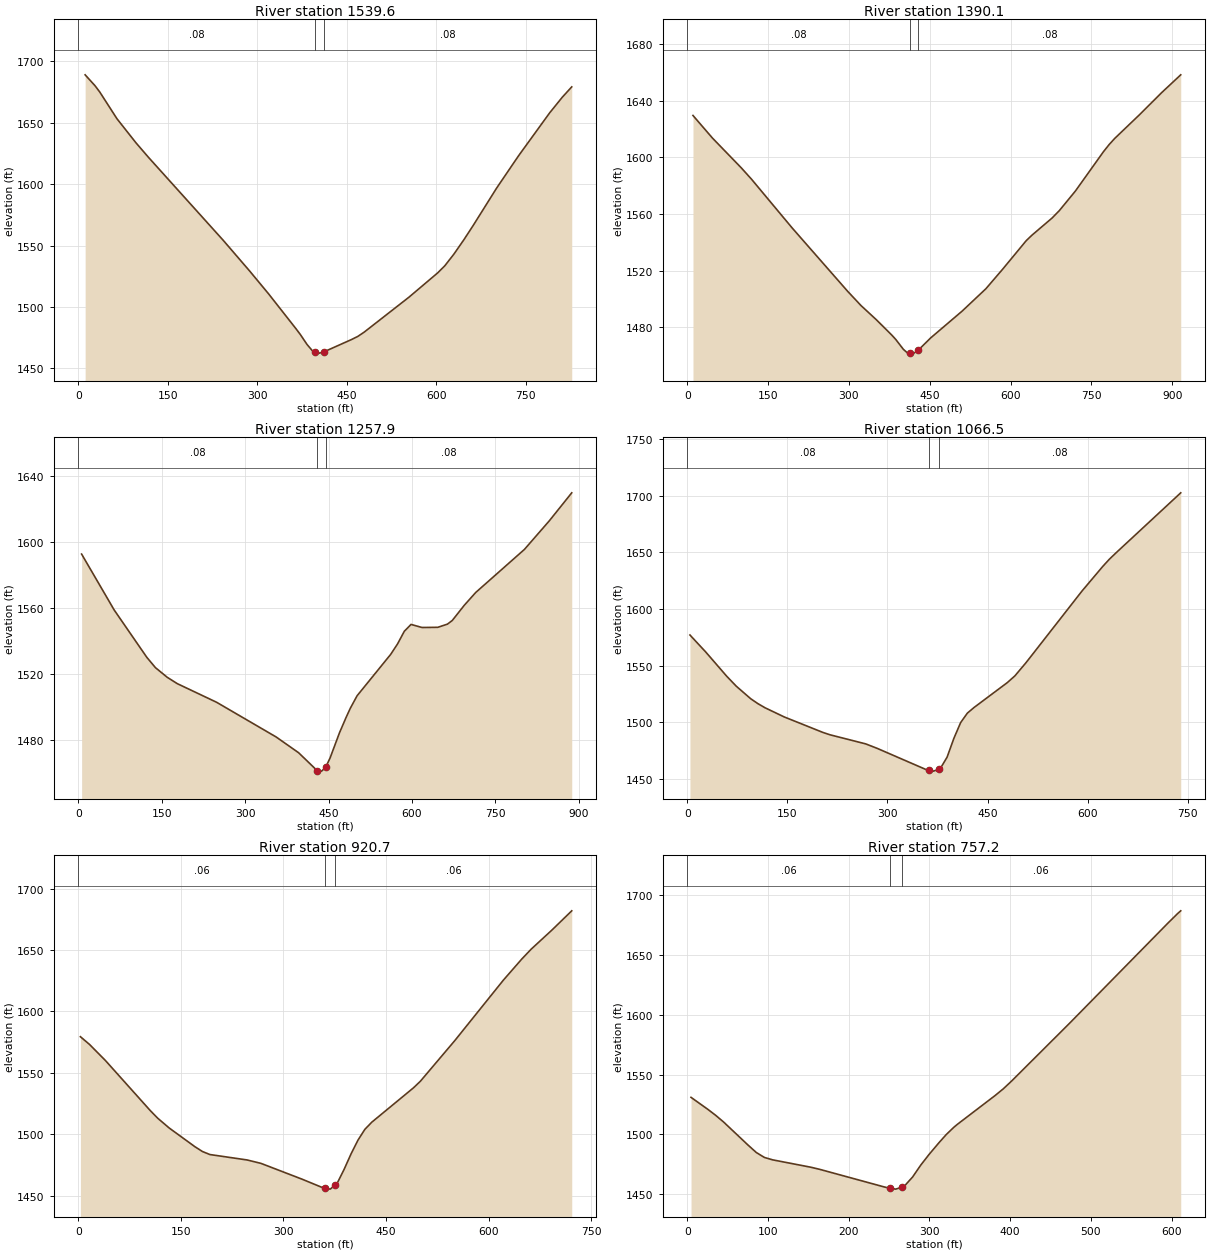
Type RM Length L Ch R = 1 ,1539.6  ,157.6,149.5,142.2
XS GIS Cut Line= 3
     1766456.529      104581.525     1766845.935      104460.244
       1767241.1      104321.478
#Sta/Elev= 30
    11.6    1689      28 1680.22    36.1    1675    64.9 1653.24    96.7 1633.67
   117.9  1621.7   242.9 1554.24   287.4 1529.11   318.8  1510.7   364.8 1482.22
   372.1 1477.51   383.4 1469.36   393.3  1463.7   396.4 1463.13   403.9 1462.37
   411.4 1463.36   457.5 1473.37   468.2 1475.93   478.9 1479.42   553.9 1507.87
   602.1 1527.69     614 1533.45     629 1542.79   645.7 1554.47   661.6 1566.31
   701.2 1597.01   737.8 1623.19   789.8 1658.08   811.2 1670.95   826.7 1679.18
#Mann= 3 , 0 , 0
       0     .08       0   396.4    .045       0   411.4     .08       0
Bank Sta=396.4,411.4
XS Rating Curve= 0 ,0
Exp/Cntr=0.3,0.1

Type RM Length L Ch R = 1 ,1390.1  ,131,132.3,133.6
XS GIS Cut Line= 4
     1766501.982      104666.753     1766824.253      104649.918
     1767004.629      104515.238     1767367.785      104455.112
#Sta/Elev= 30
    10.7 1629.53    46.9 1613.56   100.1 1592.67   119.3 1584.57     195 1550.06
   297.8 1505.45   322.7 1495.34   350.7 1485.52   379.6  1474.6   386.8  1471.6
   401.3 1464.46   408.2 1462.15   413.3 1461.96   420.8 1461.84   428.3 1463.74
   451.9  1472.6   510.4 1491.55   554.2 1507.23   585.4 1521.06   629.2 1541.21
   639.5 1544.97   677.3 1557.22   690.7 1562.44   720.4 1576.21   772.7 1604.07
   783.1 1609.03   793.2 1613.26   839.8 1630.21   879.7 1645.36   915.9 1658.21
#Mann= 3 , 0 , 0
       0     .08       0   413.3    .045       0   428.3     .08       0
Bank Sta=413.3,428.3
XS Rating Curve= 0 ,0
Exp/Cntr=0.3,0.1

Type RM Length L Ch R = 1 ,1257.9  ,179.7,191.3,203
XS GIS Cut Line= 4
     1766624.327      104925.285     1766872.354      104765.358
     1767141.714      104587.388     1767406.265      104536.883
#Sta/Elev= 30
     6.1 1592.57    64.8 1558.66   123.4 1530.04   138.8 1523.84     160 1517.99
   178.1 1514.14   248.7 1502.88   355.9 1481.85   396.3  1472.3   430.2 1461.29
   437.7 1461.18   445.2 1463.72   452.9 1469.22   469.7 1484.35   481.5  1493.6
   489.3 1499.29   501.4 1506.81   561.8 1531.86   574.1 1538.17   586.3 1545.84
   598.4 1549.99     618 1548.13   646.5 1548.24   663.8 1550.16   672.5 1552.37
     694 1561.53   714.6  1569.3   802.2 1595.38   846.8 1612.63   887.3 1629.65
#Mann= 3 , 0 , 0
       0     .08       0   430.2    .045       0   445.2     .08       0
Bank Sta=430.2,445.2
XS Rating Curve= 0 ,0
Exp/Cntr=0.3,0.1

Type RM Length L Ch R = 1 ,1066.5  ,142.6,145.8,148.9
XS GIS Cut Line= 4
     1766682.358      104969.784     1766925.264      104878.394
     1767213.865      104854.344      1767403.86      104847.129
#Sta/Elev= 30
     4.1 1577.03    27.7 1562.05    59.1 1540.66    73.5  1531.8    95.1 1520.74
   105.9 1516.39   116.7 1512.71   145.4 1504.63   203.2 1490.98     214 1488.86
   267.5 1480.83   285.1 1476.76   358.8 1457.91   361.5 1457.61     369 1456.78
   376.5 1458.38   379.1 1459.05   389.3 1469.11   399.4 1485.64   409.6 1499.65
   419.7 1508.03   429.9 1513.09   479.5 1534.97   490.8 1540.88   507.6 1552.63
   591.4 1615.87   622.5 1637.61   632.6 1644.09   642.4 1649.62   739.3 1702.62
#Mann= 3 , 0 , 0
       0     .08       0   361.5    .045       0   376.5     .08       0
Bank Sta=361.5,376.5
XS Rating Curve= 0 ,0
Exp/Cntr=0.3,0.1

Type RM Length L Ch R = 1 ,920.7   ,161.7,163.5,165.4
XS GIS Cut Line= 4
     1766683.863      105098.758     1766910.215      105007.254
     1767201.583       105024.11     1767386.999      105016.886
#Sta/Elev= 30
     3.2 1579.35    16.5 1573.07    39.8 1559.96   105.3 1519.24   116.2 1513.01
     133 1505.04   170.7 1489.77   181.6 1485.89   192.6 1483.41   246.9 1479.01
   267.2 1476.23     327 1463.43   358.4 1456.23     361 1455.96   368.5 1455.26
     376  1458.8   378.6 1459.98   388.7 1471.24   398.9 1483.92     409 1495.08
   419.1 1503.92   429.3 1509.78   490.1 1537.68   500.2 1543.04   550.5  1576.1
   621.7 1625.44   648.6  1642.6   662.2 1650.57   692.6 1666.15   721.6 1681.83
#Mann= 3 , 0 , 0
       0     .06       0     361    .045       0     376     .06       0
Bank Sta=361,376
XS Rating Curve= 0 ,0
Exp/Cntr=0.3,0.1

Type RM Length L Ch R = 1 ,757.2   ,132.6,134.2,135.8
XS GIS Cut Line= 4
     1766746.471      105154.142     1766886.135      105158.958
     1767194.359      105202.302     1767353.287      105223.974
#Sta/Elev= 30
     4.7 1530.97    25.3 1521.07      35 1516.09    45.1 1510.34    75.5 1491.01
    85.6 1484.89    95.7 1480.74   105.9 1478.75   153.5 1472.55   164.4 1470.78
   244.1 1456.12   250.7  1455.1   258.2  1454.3   265.7 1455.84     269 1456.56
   271.4  1458.6   279.2 1464.41   289.4 1474.44   299.6 1483.26   311.9 1493.08
   320.9 1499.88   330.3 1505.95   334.8 1508.48   381.3 1532.42   391.6  1538.1
   401.8 1544.54   473.4 1592.67   595.8 1676.69   607.9 1684.71   611.4 1686.77
#Mann= 3 , 0 , 0
       0     .06       0   250.7    .045       0   265.7     .06       0
Bank Sta=250.7,265.7
XS Rating Curve= 0 ,0
Exp/Cntr=0.3,0.1

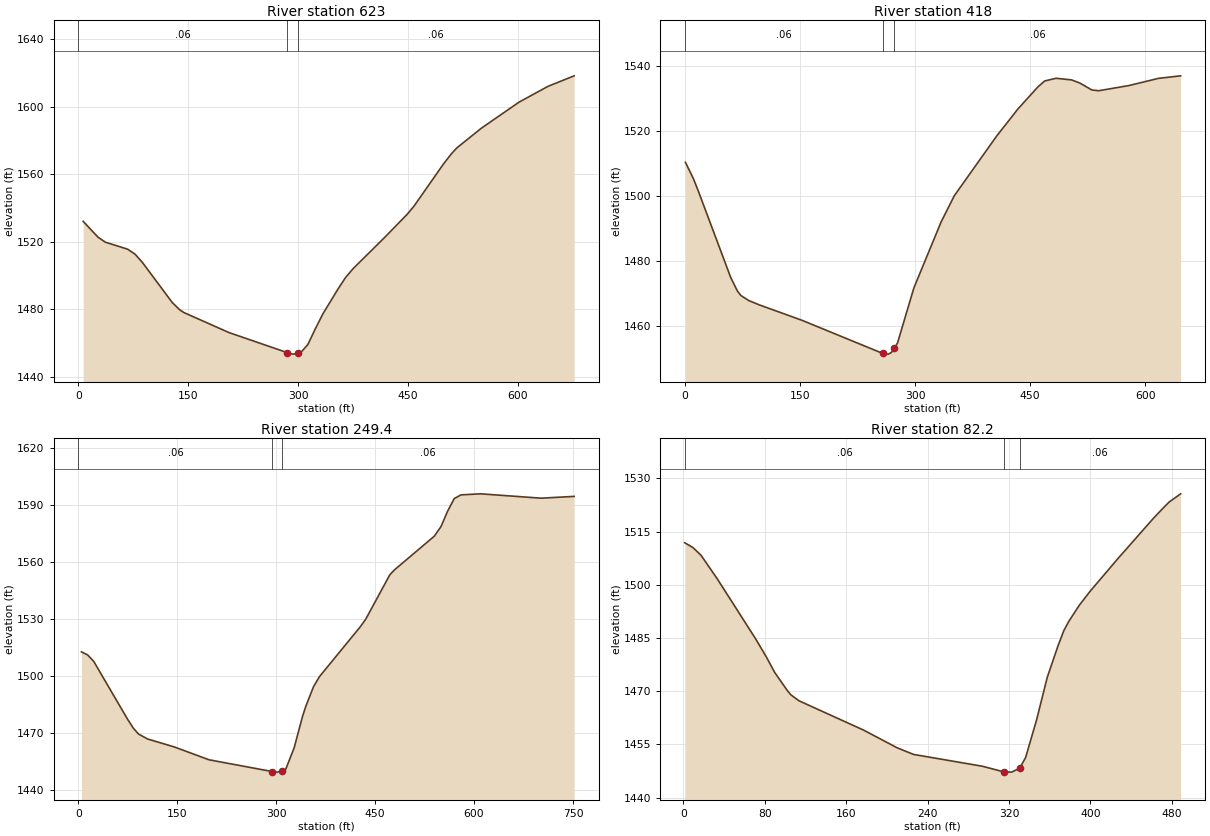
Type RM Length L Ch R = 1 ,623     ,201.4,205.1,208.8
XS GIS Cut Line= 4
     1766683.863      105274.542     1766859.647      105281.766
     1767095.631      105332.334     1767350.879      105378.086
#Sta/Elev= 30
     6.6 1532.08    26.8 1522.74    36.9 1519.75    67.3 1515.61    77.4 1512.67
    87.6 1507.69   128.1  1484.1   138.2 1479.79   143.9 1478.16   205.7 1466.27
     285 1454.45   292.5 1453.54     300 1453.98   302.9 1454.15   313.2 1459.21
   323.6 1468.68   333.9 1477.48   354.6 1492.22   364.9    1499   375.3 1504.26
   416.7    1522   448.7 1536.22   457.8 1540.93   498.7 1566.26   509.2 1572.09
   516.4 1575.47   549.6 1587.05   601.6 1602.64   640.9 1611.93   676.6 1618.15
#Mann= 3 , 0 , 0
       0     .06       0     285    .045       0     300     .06       0
Bank Sta=285,300
XS Rating Curve= 0 ,0
Exp/Cntr=0.3,0.1

Type RM Length L Ch R = 1 ,418     ,162.1,168.6,175.1
XS GIS Cut Line= 5
     1766669.415      105428.654     1766799.447      105455.142
     1766986.762      105528.667     1767084.876      105537.308
     1767295.495      105573.134
#Sta/Elev= 30
      .8 1510.31    11.1 1505.36    17.1  1501.8    59.9  1474.9    68.5 1470.81
    73.1  1469.4    83.4 1467.85    96.9 1466.54   152.6  1461.8     258 1451.61
   265.5  1451.4   269.4 1451.97     273 1453.19   277.2 1454.82   298.1 1471.41
   300.6 1472.93   333.9 1491.94   351.2 1500.05   406.1 1518.28   433.9 1526.64
   460.3 1533.51     469 1535.29   483.8 1536.12   504.1 1535.61   514.6 1534.68
   530.4 1532.53   539.2 1532.29   578.7 1533.88   617.2 1536.09   646.1 1536.87
#Mann= 3 , 0 , 0
       0     .06       0     258    .045       0     273     .06       0
Bank Sta=258,273
XS Rating Curve= 0 ,0
Exp/Cntr=0.3,0.1

Type RM Length L Ch R = 1 ,249.4   ,153.6,167.2,180.8
XS GIS Cut Line= 4
     1766640.519      105440.694     1766784.999       105602.03
     1766987.271       105758.55     1767266.599      105765.774
#Sta/Elev= 30
     4.7 1512.74    14.2  1511.1    23.4  1507.7    74.8 1477.24    83.5 1472.58
    91.3 1469.52   105.1 1466.92   145.6 1462.74   198.1    1456   294.1 1449.81
   301.6 1449.51   309.1 1450.12   314.4 1450.98   327.2 1462.21     340 1478.86
     345 1484.17   356.6 1494.43   365.6  1499.7   427.7    1526   435.9    1530
   472.3 1553.24   478.9  1555.7   539.7 1573.53   549.8 1578.54   559.9 1586.65
     570 1593.33   580.2 1595.26   609.9 1595.81   701.6 1593.52   751.8 1594.46
#Mann= 3 , 0 , 0
       0     .06       0   294.1    .045       0   309.1     .06       0
Bank Sta=294.1,309.1
XS Rating Curve= 0 ,0
Exp/Cntr=0.3,0.1

Type RM Length L Ch R = 1 ,82.2    ,82.2,82.2,82.1
XS GIS Cut Line= 5
     1766634.685      105461.678     1766671.762      105576.362
     1766749.749      105817.588     1766738.679      105864.361
     1766723.323       105929.24
#Sta/Elev= 30
     1.3 1511.85     9.3  1510.5    17.3 1508.32    33.4 1501.61    70.7 1484.88
    81.3 1479.77    89.6 1475.34   102.5 1470.05   105.7 1468.97   113.7 1467.29
     177 1459.06   210.1 1454.06   226.2 1452.19   293.9 1448.86   315.1 1447.26
   322.6  1447.2   330.6 1448.31   336.4 1451.32   347.1 1461.83   357.7 1473.95
   368.3 1482.84     374 1487.11   378.8 1489.66   389.2 1494.25   399.6 1498.11
   427.2 1507.41     462 1518.73   472.4 1521.87   477.5 1523.33   488.8 1525.65
#Mann= 3 , 0 , 0
     1.3     .06       0   315.1    .045       0   330.6     .06       0
Bank Sta=315.1,330.6
XS Rating Curve= 0 ,0
Exp/Cntr=0.3,0.1

Chan Stop Cuts=-1
Use User Specified Reach Order=0